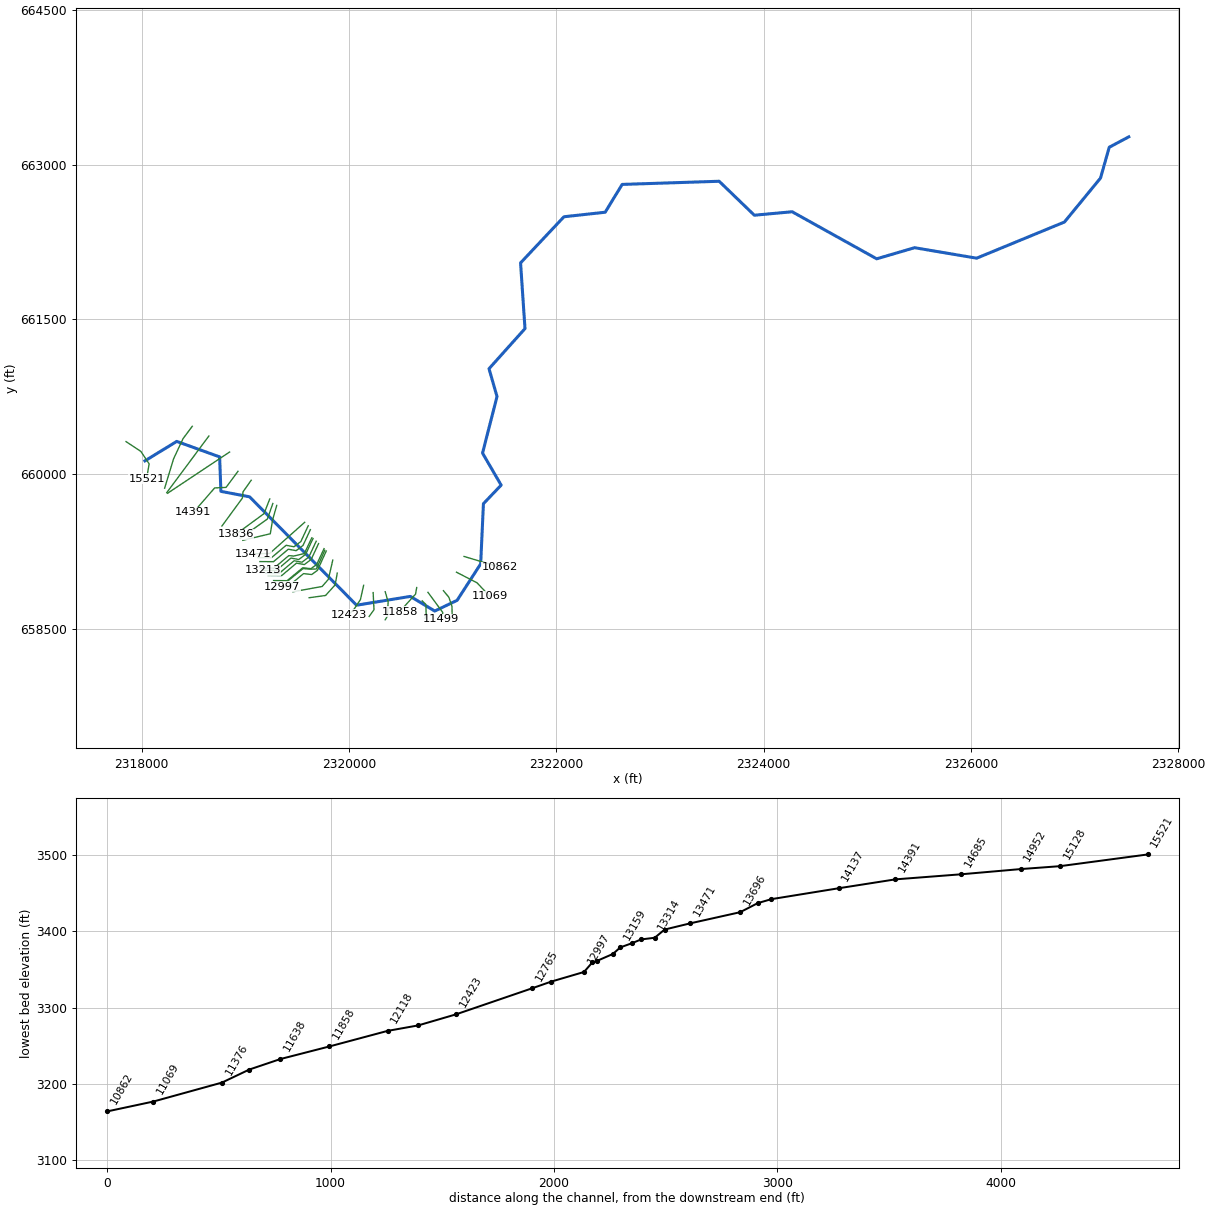
--- FISHHAWKCK.prj (project) ---

Proj Title=FISHHAWKCK
Current Plan=p01
Default Exp/Contr=0,0
English Units
Geom File=g01
Flow File=f01
Plan File=p01
Background Map Layer=Inundation Boundary (P100yr Value_0)
BEGIN DESCRIPTION:
----------MODEL BY WOOD PLC 2022----------
AFH study
Randolph County, WV
HEC-RAS Version: RAS 6.2
Vertical Datum: NAVD88
Projection: NAD 1983 StatePlane West Virginia S FIPS 4702 (US Feet)
Terrain: 1-meter LIDAR (FEMA Region III 3DEP collected 2016-2018)
Land Use: 2019 NLCD
Hydrologic Method:
WV SIR2010-5033 regression equations
Additional Model Notes:
None
END DESCRIPTION:
DSS Export Rating Curves= 0
DSS Export Rating Curve Sorted= 0
DSS Export Volume Flow Curves= 0
DXF OffsetX= 0
DXF OffsetY= 0
DXF ScaleX= 0
DXF ScaleY= 0

--- FISHHAWKCK.p01 (plan) ---

Plan Title=Floodplain
Program Version=6.20
Short Identifier=Floodplain
Geom File=g01
Flow File=f01
Subcritical Flow
K Sum by GR= 0
Std Step Tol= 0.01
Critical Tol= 0.01
Num of Std Step Trials= 20
Max Error Tol= 0.3
Flow Tol Ratio= 0.001
Split Flow NTrial= 30
Split Flow Tol= 0.02
Split Flow Ratio= 0.02
Log Output Level= 0
Friction Slope Method= 1
Unsteady Friction Slope Method= 2
Unsteady Bridges Friction Slope Method= 1
Parabolic Critical Depth
Global Vel Dist= 0 , 0 , 0
Global Log Level= 0
CheckData=False
Encroach Param=-1 ,0,0, 0
Mapping Interval=1HOUR
Computation Time Step Use Courant=        0
Computation Time Step Use Time Series=    0
Computation Time Step Count To Double=0
Computation Time Step Max Doubling=0
Computation Time Step Max Halving=0
Computation Time Step Residence Courant=0
Run HTab= 0
Run UNet= 0
Run Sediment= 0
Run PostProcess= 0
Run WQNet= 0
Run RASMapper=-1
UNET Theta= 0
UNET Theta Warmup= 0
UNET ZTol= 0
UNET ZSATol= 0
UNET MxIter= 0
UNET Max Iter WO Improvement= 0
UNET MaxInSteps= 0
UNET DtIC= 0
UNET DtMin= 0
UNET MaxCRTS= 0
UNET WFStab= 0
UNET SFStab= 0
UNET WFX= 1
UNET SFX= 1
UNET Gravity=32.174
UNET 1D Methodology=Finite Difference
UNET DSS MLevel= 1
UNET Pardiso=0
UNET DZMax Abort= 0
UNET Use Existing IB Tables= 0
UNET Froude Reduction=False
UNET Froude Limit= 0
UNET Froude Power= 0
UNET D1 Cores= 0
UNET WindReference=Eulerian
UNET WindDragFormulation=Hsu (1988)
UNET D2 Coriolis=0
UNET D2 Cores= 0
UNET D2 Theta= 1
UNET D2 Theta Warmup= 1
UNET D2 Z Tol= 0.01
UNET D2 Volume Tol= 0.01
UNET D2 Max Iterations= 20
UNET D2 Equation= 0
UNET D2 RampUpFraction=0.1
UNET D2 TimeSlices= 1
UNET D2 Turbulence Formulation=Non-Conservative (original)
UNET D2 Eddy Viscosity=0.3
UNET D2 Transverse Eddy Viscosity=0.1
UNET D2 Smagorinsky Mixing=0
UNET D2 BCVolumeCheck=0
UNET D2 Cores=0
UNET D2 SolverType=PARDISO (Direct)
UNET D2 Minimum Iterations= 2147483647
UNET D2 Maximum Iterations= 2147483647
UNET D2 Restart Number= 10
UNET D2 Relaxation Coeff=1.3
UNET D2 SOR Precondition Iterations= 10
UNET D2 ILUT Maximum Fill= 8
UNET D2 ILUT Tolerance=1E-08
UNET D1D2 MaxIter= 0
UNET D1D2 ZTol=0.01
UNET D1D2 QTol=0.1
UNET D1D2 MinQTol=1
Write IC File= 0
Write IC File at Fixed DateTime=0
Write IC File at Sim End=0
Echo Input=False
Echo Parameters=False
Echo Output=False
Write Detailed= 0
HDF Write Warmup=0
HDF Write Time Slices=0
HDF Flush=0
HDF Compression= 1
HDF Chunk Size= 1
HDF Spatial Parts= 1
HDF Use Max Rows=0
HDF Fixed Rows= 1
Calibration Method= 0
Calibration Iterations= 20
Calibration Max Change=0.05
Calibration Tolerance=0.2
Calibration Maximum=1.5
Calibration Minimum=0.5
Calibration Optimization Method= 1
WQ AD Non Conservative
WQ ULTIMATE=-1
WQ Max Comp Step=1HOUR
WQ Output Interval=15MIN
WQ Output Selected Increments= 0
WQ Output face flow=0
WQ Output face velocity=0
WQ Output face area=0
WQ Output face dispersion=0
WQ Output cell volume=0
WQ Output cell surface area=0
WQ Output cell continuity=0
WQ Output cumulative cell continuity=0
WQ Output face conc=0
WQ Output face dconc_dx=0
WQ Output face courant=0
WQ Output face peclet=0
WQ Output face adv mass=0
WQ Output face disp mass=0
WQ Output cell mass=0
WQ Output cell source sink temp=0
WQ Output nsm pathways=0
WQ Output nsm derived pathways=0
WQ Create Restart=0
WQ Fixed Restart=0
WQ System Summary=0
WQ Write To DSS=0
Sorting and Armoring Iterations= 10
XS Update Threshold= 0.02
Bed Roughness Predictor= 0
Hydraulics Update Threshold= 0.02
Energy Slope Method= 1
Volume Change Method= 1
Sediment Retention Method= 0
Sediment TS Multiplier= 1
Warm Up Method= 0
XS Weighting Method= 0
Number of US Weighted Cross Sections= 1
Number of DS Weighted Cross Sections= 1
Upstream XS Weight=0
Main XS Weight=1
Downstream XS Weight=0
Number of DS XS's Weighted with US Boundary= 1
Upstream Boundary Weight= 1
Weight of XSs Associated with US Boundary= 0
Number of US XS's Weighted with DS Boundary= 1
Downstream Boundary Weight= 0.5
Weight of XSs Associated with DS Boundary= 0.5
Percentile Method= 0
Sediment Output Level= 3
Mass or Volume Output= 0
Output Increment Type= 1
Profile and TS Output Increment= 1
Transport Output Increment 1
XS Output Flag= 0
XS Output Increment= 10
Read HDF5 Sediment Hotstart= 0
Sediment Hotstart Type= 0
Write Gradation File= 0
Read Gradation Hotstart= 0
Write HDF5 File= 1
Write Binary Output= 1
Write DSS Sediment File= 0
DSS Sediment Output Type= 1
SV Curve= 0
Specific Gage Flag= 0
Subcell Erosion Methods= 0
Subcell Deposition Methods= 0
Advection Scheme= 1
Matrix Solver= 0
Implicit Weighting Factor= 1
Maximum Outer Loop Convergence Iterations= 5
Convergence Maximum Absolute= 0.001
Convergence RMSE= 0.0001
Grain Fractions Max Abs Error= 0.001
Max Subgrid Regions= 1
Max Subgrid Length Scale= 3.402823E+38
Initial Layer Thickness= 3.402823E+38
Min Layer Thickness= 3.402823E+38
Max Layer Thickness= 3.402823E+38
Number of Layers= 5

--- FISHHAWKCK.f01 (steady flow) ---

Flow Title=Flow
Program Version=6.20
Number of Profiles= 1
Profile Names=P100yr
River Rch & RM=FISHHAWKCK,Main,15521
     472
River Rch & RM=FISHHAWKCK,Main,10862
     531
River Rch & RM=FISHHAWKCK,Main,7608
     668
River Rch & RM=FISHHAWKCK,Main,5204
    1080
Boundary for River Rch & Prof#=FISHHAWKCK,Main            , 1
Up Type= 0
Dn Type= 3
Dn Slope=0.078
DSS Import GetInterval= 0
DSS Import GetPeak= 0
DSS Import FillOption= 0

--- FISHHAWKCK.g01 (geometry) ---

Geom Title=Geometry
Program Version=6.20

River Reach=FISHHAWKCK      ,Main
Reach XY= 30
2318030.77700001660131.5370000152318337.54700002660319.819000006
2318751.08900002660169.819000006     2318763.589659836.225000009
     2319040.412659783.3599999992320072.38429209658734.159299413
2320591.22199999658819.3320000172320826.89900005658677.665999994
2321042.52399999658781.3120000212321269.86800005659134.175999999
2321296.43000001659716.9889999932321467.48100002659896.306999996
2321287.79300001660206.4630000142321427.59254239660754.047605222
2321350.32693101661023.6366883012321697.38813395661411.490216785
2321654.74300002662047.8390000162322073.45799999662494.488000005
2322471.12395172662538.2271052732322634.96500002662807.512000009
2323570.79128829662838.0151351632323910.27000003662509.343999997
2324275.09900002      662542.8092325090.76000001 662087.36300002
2325456.36000003662194.840000004     2326055.184662093.408000007
2326902.02100001662443.2720000152327250.00100003662868.776999995
     2327334.574 663167.424000012327522.84696178663267.935375451

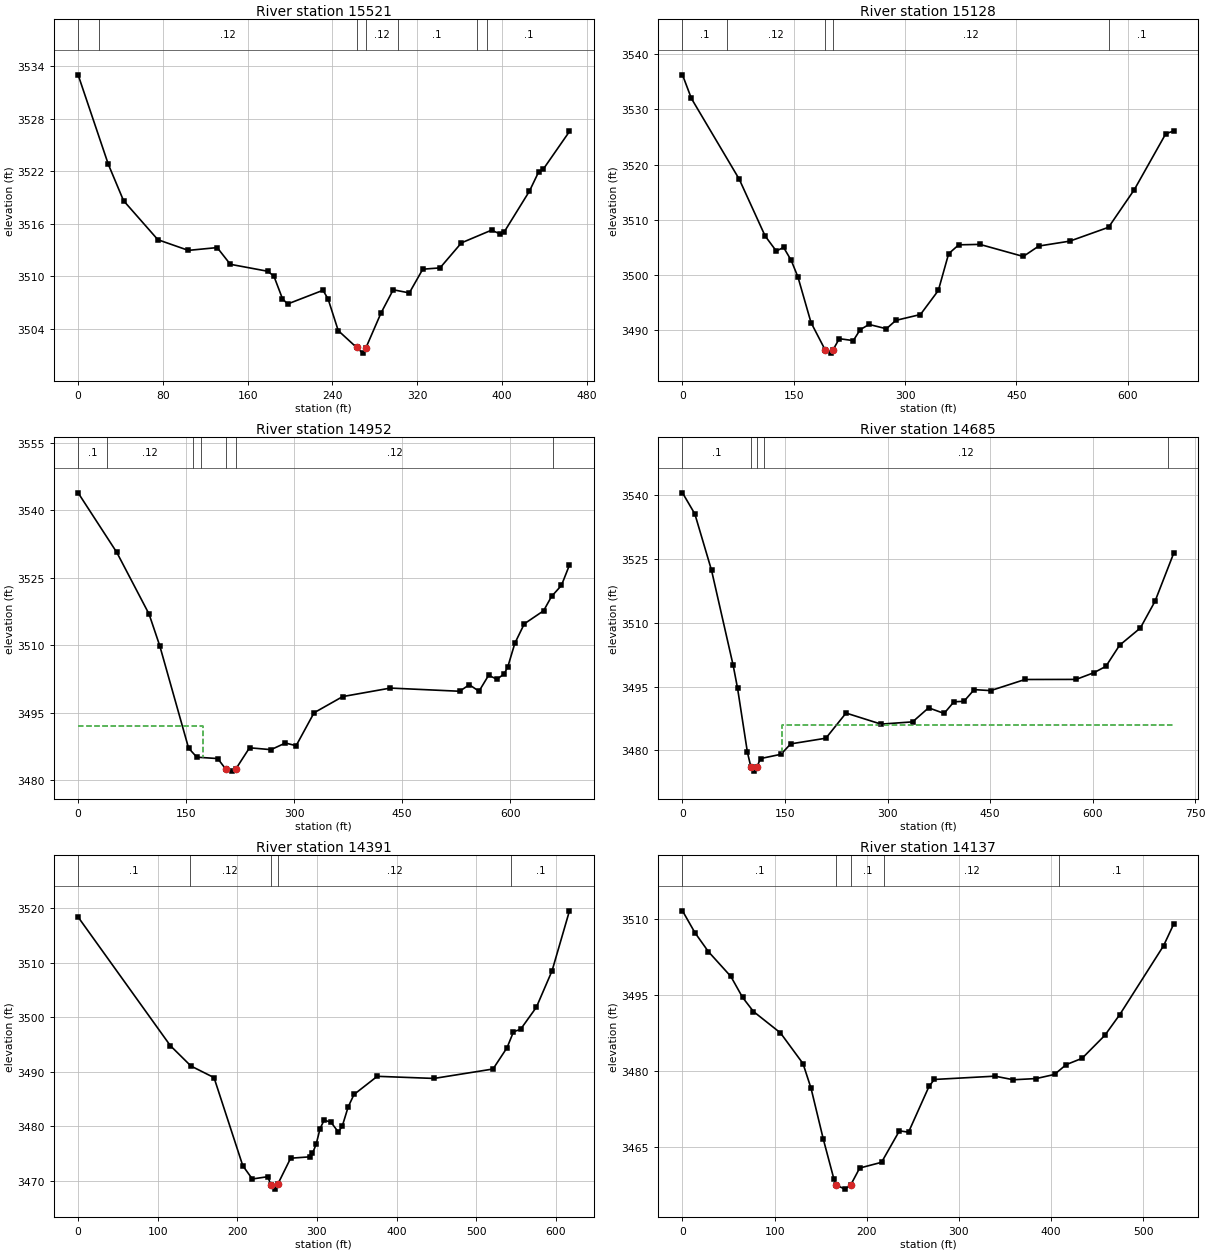
Type RM Length L Ch R = 1 ,15521   ,395,392.7,384.6
XS GIS Cut Line= 4
2317848.41471146660317.7764745742317991.45758544660222.861399511
2318071.12335832660102.349281501 2318046.6791063659956.661539449
#Sta/Elev= 30
       0    3533    28.5 3522.78    42.9 3518.62    75.3 3514.16   104.1 3512.94
   131.3 3513.26   143.7 3511.35   179.2 3510.55   184.9 3509.98   192.9 3507.43
   197.7 3506.81   231.2 3508.38     236 3507.39   245.6 3503.77   262.9 3501.85
   268.7  3501.2   271.83501.826     286 3505.79   297.5 3508.44   312.7 3508.08
   325.4 3510.79   341.7 3510.94   361.9  3513.8   390.3 3515.25   398.4 3514.82
   402.5 3515.09   426.1 3519.71   434.9 3521.93     439 3522.19   463.9 3526.53
#Mann= 7 ,-1,0
       0      .1       0      20     .12       0   262.9    .045       0
   271.8     .12       0  301.67      .1       0  376.13     .12       0
  386.13      .1       0
Bank Sta=262.9,271.8
XS Rating Curve= 0 ,0
Exp/Cntr(USF)=0,0
Exp/Cntr=0.3,0.1

Type RM Length L Ch R = 1 ,15128   ,176.8,176.2,174.7
XS GIS Cut Line= 4
2318487.62212414660466.5901475752318398.12682864660346.207095216
 2318307.0475456660151.3766288982318220.72022516659867.050867075
#Sta/Elev= 30
       0 3536.28      12    3532    76.5 3517.35   111.4 3507.05   126.4 3504.33
   136.3 3504.98   146.6 3502.61   155.6 3499.62   173.2 3491.36   192.63486.312
   199.7 3485.81   202.63486.325   211.3 3488.43   230.2 3488.08   239.6 3490.08
   251.5 3491.01   274.8 3490.23   287.6 3491.75   320.7 3492.81   344.8 3497.17
   358.7 3503.84   372.3 3505.45   400.8 3505.53   459.3 3503.34   480.2 3505.23
     522 3506.12   574.2 3508.63     609 3515.47   651.3 3525.59   662.2 3526.11
#Mann= 5 ,-1,0
       0      .1       0      60     .12       0   192.6    .045       0
   202.6     .12       0  575.07      .1       0
Bank Sta=192.6,202.6
XS Rating Curve= 0 ,0
Exp/Cntr(USF)=0,0
Exp/Cntr=0.3,0.1

Type RM Length L Ch R = 1 ,14952   ,263.8,266.1,264.1
XS GIS Cut Line= 2
2318647.60486478660372.3428894782318241.31206306659824.283203737
#Sta/Elev= 30
       0 3543.84    53.7  3530.6    98.5 3516.89   113.4 3509.82   153.4  3487.1
   164.8 3485.09   193.8 3484.78   204.9 3482.46   213.1 3481.99   219.2 3482.52
     238 3487.18   267.8 3486.76   287.8 3488.24   302.7 3487.64   327.6 3494.96
   367.4 3498.56   433.6 3500.45   529.7 3499.74   543.1 3501.19   556.6 3499.75
     570  3503.3   581.5  3502.4   591.5  3503.6   596.5 3505.13   606.4 3510.42
   619.5 3514.73   646.3 3517.63   657.3 3520.81     671 3523.25   682.2  3527.8
#Mann= 7 ,-1,0
       0      .1       0      40     .12       0     160      .1       0
     170     .12       0   204.9    .045       0   219.2     .12       0
     660      .1       0
#XS Ineff= 2 , 0
          173.41 3491.95
Permanent Ineff=
       F       F
Bank Sta=204.9,219.2
XS Rating Curve= 0 ,0
Exp/Cntr(USF)=0,0
Exp/Cntr=0.3,0.1

Type RM Length L Ch R = 1 ,14685   ,296,294.7,291.4
XS GIS Cut Line= 2
2318847.18729369660217.1121114362318249.23200072659817.947253613
#Sta/Elev= 30
       0 3540.51    18.1 3535.55    42.5 3522.32    74.2 3499.96    80.6  3494.6
      95 3479.58   100.2 3476.05   104.6 3475.15   108.8  3476.1   114.2  3478.1
     144  3479.1   158.4 3481.55   209.8 3482.88   239.3 3488.79   290.5 3486.19
   336.7 3486.72   360.1 3490.02   382.8  3488.7   397.2 3491.44   411.7 3491.53
   426.8 3494.29   450.9 3494.06   501.1 3496.67   575.9 3496.69     602 3498.27
   619.5 3499.76   639.5 3504.71   669.9 3508.76   691.4 3515.05   718.9 3526.41
#Mann= 5 ,-1,0
       0      .1       0   100.2    .045       0   108.8      .1       0
     120     .12       0     710      .1       0
#XS Ineff= 2 , 0
                          145.72            3486
Permanent Ineff=
       F       F
Bank Sta=100.2,108.8
XS Rating Curve= 0 ,0
Exp/Cntr(USF)=0,0
Exp/Cntr=0.3,0.1

Type RM Length L Ch R = 1 ,14391   ,243.4,254.1,257.4
XS GIS Cut Line= 4
2318928.46932051660030.3775813872318813.19022798659874.618807501
2318703.19109388659869.3388490642318498.15270791659632.620712481
#Sta/Elev= 30
       0 3518.37   115.9 3494.77   141.7 3491.05   170.7 3488.92   206.8 3472.77
   218.8 3470.33   238.2 3470.75     242  3469.3   246.9 3468.47   250.63469.323
   266.9 3474.14   290.9 3474.39   294.3 3475.03   298.9 3476.67   303.9 3479.58
     309 3481.12   317.5 3480.75   326.8 3478.95   331.7 3479.99   339.1 3483.52
   346.5 3485.83   375.7 3489.16     447 3488.77   521.1  3490.5   538.7 3494.41
   546.8 3497.33   555.7 3497.78   575.5 3501.82   595.2  3508.5   617.1 3519.51
#Mann= 5 ,-1,0
       0      .1       0     140     .12       0     242    .045       0
   250.6     .12       0   543.9      .1       0
Bank Sta=242,250.6
XS Rating Curve= 0 ,0
Exp/Cntr(USF)=0,0
Exp/Cntr=0.3,0.1

Type RM Length L Ch R = 1 ,14137   ,306.5,300.8,294.3
XS GIS Cut Line= 4
2319056.06831607659944.1382602532318976.86893952659831.499146934
2318970.70898801659770.779624911 2318773.5905397 659500.62175156
#Sta/Elev= 30
       0 3511.57    13.5 3507.27    28.1 3503.54    52.5 3498.65    65.2 3494.53
      77 3491.75   106.3 3487.54   130.8 3481.49   139.5 3476.64   152.9 3466.56
   164.2 3458.85     1673457.566   176.2 3456.78   182.53457.583   192.3 3460.93
     216 3462.06   235.4 3468.26   245.3 3467.99   267.5 3476.99   273.3 3478.37
   339.1 3479.02   359.1 3478.31   383.9 3478.55   403.7 3479.36   416.4 3481.29
   433.6 3482.53   458.2 3487.03   474.5 3491.13     522 3504.68   533.2 3509.02
#Mann= 5 ,-1,0
       0      .1       0     167    .045       0   182.5      .1       0
  218.73     .12       0  408.73      .1       0
Bank Sta=167,182.5
XS Rating Curve= 0 ,0
Exp/Cntr(USF)=0,0
Exp/Cntr=0.3,0.1

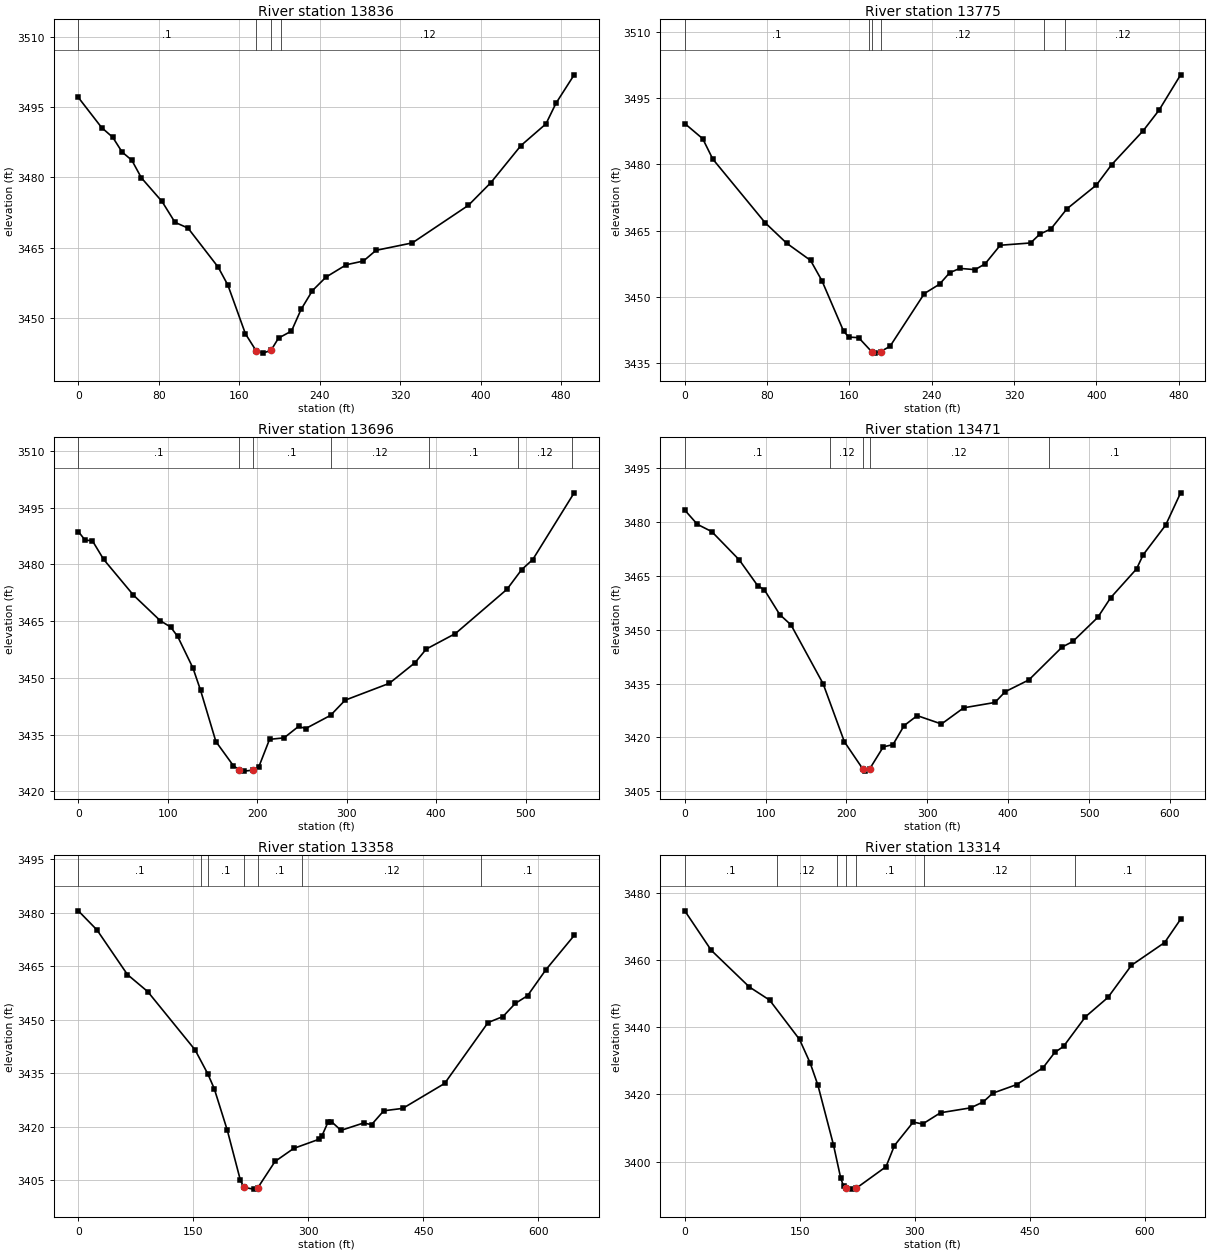
Type RM Length L Ch R = 1 ,13836   ,61.2,61,61
XS GIS Cut Line= 3
2319234.70690985659762.8596872552319180.14733933659621.180802534
2318905.58950062 659418.78239579
#Sta/Elev= 30
       0 3497.07    23.2 3490.63    34.2 3488.57    43.5 3485.42    53.2 3483.66
    62.7  3479.9    83.2 3474.86    96.1 3470.41     109 3469.19     139 3460.85
   148.7 3456.99   166.1 3446.62   176.6 3443.04   183.3 3442.49   191.5 3443.07
     199  3445.7   211.9  3447.2   221.4 3451.81   232.7 3455.83   246.2 3458.72
   266.4 3461.36   283.4 3462.15   295.9 3464.43     332 3466.02   387.8 3474.05
   410.2 3478.91     440  3486.8   464.9 3491.44   474.8 3495.82   492.9  3501.9
#Mann= 4 ,-1,0
       0      .1       0   176.6    .045       0   191.5      .1       0
  201.82     .12       0
Bank Sta=176.6,191.5
XS Rating Curve= 0 ,0
Exp/Cntr(USF)=0,0
Exp/Cntr=0.3,0.1

Type RM Length L Ch R = 1 ,13775   ,72.4,78.8,81.4
XS GIS Cut Line= 3
2319264.62667432659718.8600336152319211.82708996659568.381218166
2318949.58915426659380.942693659
#Sta/Elev= 30
       0 3489.24    17.4 3485.81    27.2  3481.2    78.1 3466.78      99 3462.15
   122.2 3458.26   133.2 3453.69   154.4 3442.19   159.5 3440.89   168.9 3440.78
   181.6 3437.59   184.5 3437.27   190.2 3437.62   199.4  3438.8   232.8 3450.76
   247.5 3452.87   257.4 3455.47   267.2 3456.45   282.1 3456.17   291.8 3457.48
   306.5 3461.69     336 3462.21     345 3464.21   355.7 3465.37   371.3 3469.93
     400 3475.33   414.7 3479.91   445.4 3487.61   460.8 3492.26   481.8 3500.27
#Mann= 6 ,-1,0
       0      .1       0  179.47     .12       0   181.6    .045       0
   190.2     .12       0  349.47      .1       0  369.47     .12       0
Bank Sta=181.6,190.2
XS Rating Curve= 0 ,0
Exp/Cntr(USF)=0,0
Exp/Cntr=0.3,0.1

Type RM Length L Ch R = 1 ,13696   ,229.6,224.7,220.2
XS GIS Cut Line= 4
2319302.46637645659700.3801790862319262.86668818659563.101259729
2319239.98686829659425.8223403722318975.10895337 659362.46283913
#Sta/Elev= 30
       0 3488.66     7.5 3486.42    15.8 3486.21    28.3 3481.31    61.6 3471.87
    91.7 3465.09   103.2 3463.43   111.1 3460.93   128.2 3452.58   136.6 3446.77
   153.8 3433.17   173.2 3426.83   180.2 3425.61   185.1 3425.35   195.5 3425.61
   201.6 3426.35   213.8 3433.75     230 3434.14   246.2 3437.16   254.3 3436.61
     282 3440.09   298.3  3444.1   347.7 3448.55   376.5 3454.02     389  3457.6
   421.7 3461.72   479.3 3473.41   495.7  3478.6   508.1 3481.26   554.4  3498.9
#Mann= 7 ,-1,0
       0      .1       0   180.2    .045       0   195.5      .1       0
  282.05     .12       0  392.05      .1       0  492.05     .12       0
  552.05      .1       0
Bank Sta=180.2,195.5
XS Rating Curve= 0 ,0
Exp/Cntr(USF)=0,0
Exp/Cntr=0.3,0.1

Type RM Length L Ch R = 1 ,13471   ,113.7,113.6,110.8
XS GIS Cut Line= 3
2319571.74425673659536.7014675452319233.82691678659234.863843574
2319073.66817753659232.223864355
#Sta/Elev= 30
       0 3483.34    15.5 3479.39    33.4 3477.35    67.3 3469.49      90 3462.34
    98.5 3461.12   117.4 3454.26   131.4 3451.36   171.1 3434.97   197.4 3418.81
   220.3  3411.2   223.2 3410.63   228.5 3411.19   245.5 3417.38   257.5 3418.02
   271.3 3423.32   287.5 3426.09   317.5 3423.76     345 3428.27   383.6 3429.76
   396.3 3432.75   425.6 3436.04   466.7 3445.19     480 3446.75   510.8 3453.46
   526.8 3458.95   558.8 3466.97     567 3470.91   594.8 3479.17   613.3 3488.16
#Mann= 5 ,-1,0
       0      .1       0     180     .12       0   220.3    .045       0
   228.5     .12       0     450      .1       0
Bank Sta=220.3,228.5
XS Rating Curve= 0 ,0
Exp/Cntr(USF)=0,0
Exp/Cntr=0.3,0.1

Type RM Length L Ch R = 1 ,13358   ,43.1,44,43.6
XS GIS Cut Line= 6
2319606.06398657659503.2617307792319534.78454767659350.142936111
2319468.78506721659299.9833309612319393.10566295659314.063220126
2319250.54678516659193.5041691522319119.42781731659194.384162225
#Sta/Elev= 30
       0  3480.5    24.4 3475.12    64.1 3462.63    90.5 3457.87   152.3 3441.53
   168.9  3434.8   177.2 3430.71   194.3 3419.01   211.4 3404.97   216.13403.016
   228.5 3402.54   234.2 3402.97   256.5 3410.29   280.9 3413.95   313.4 3416.47
   317.5 3417.38   325.6 3421.29   330.1 3421.45   342.5    3419   371.9 3421.06
   382.4 3420.61   398.3 3424.49   423.1 3425.16   477.7 3432.15   534.3  3449.2
   553.8 3450.89   569.8 3454.56   585.8 3456.72   609.8 3464.02   646.6 3473.59
#Mann= 7 ,-1,0
       0      .1       0     160     .12       0   168.9      .1       0
   216.1    .045       0   234.2      .1       0  291.79     .12       0
  525.47      .1       0
Bank Sta=216.1,234.2
XS Rating Curve= 0 ,0
Exp/Cntr(USF)=0,0
Exp/Cntr=0.3,0.1

Type RM Length L Ch R = 1 ,13314   ,66.6,61.7,60.4
XS GIS Cut Line= 6
2319626.74382378659465.4220286482319555.46438488 659312.30323398
2319489.46490442659262.1436288312319413.78550016659276.223517996
2319271.22662237659155.6644670222319140.10765452659156.544460095
#Sta/Elev= 30
       0 3474.71    34.5 3462.95    84.1 3452.04   110.6 3448.11   149.6  3436.4
   163.5 3429.36   173.5 3422.82   193.9 3404.96   203.2  3395.2   207.1 3392.59
   210.1 3392.02   218.2 3391.79   223.3 3392.01   262.4 3398.47   273.4 3404.78
   297.9 3411.77   310.1 3411.19   333.5 3414.55   372.8 3416.01   389.2 3417.77
   401.6 3420.38   432.6 3422.92   467.1 3427.94   482.5 3432.53   493.9 3434.31
   522.5 3443.14   551.8  3448.9   582.5 3458.49   625.8 3465.27   646.6 3472.21
#Mann= 7 ,-1,0
       0      .1       0     120     .12       0   198.9      .1       0
   210.1    .045       0   223.3      .1       0  311.79     .12       0
  508.77      .1       0
Bank Sta=210.1,223.3
XS Rating Curve= 0 ,0
Exp/Cntr(USF)=0,0
Exp/Cntr=0.3,0.1

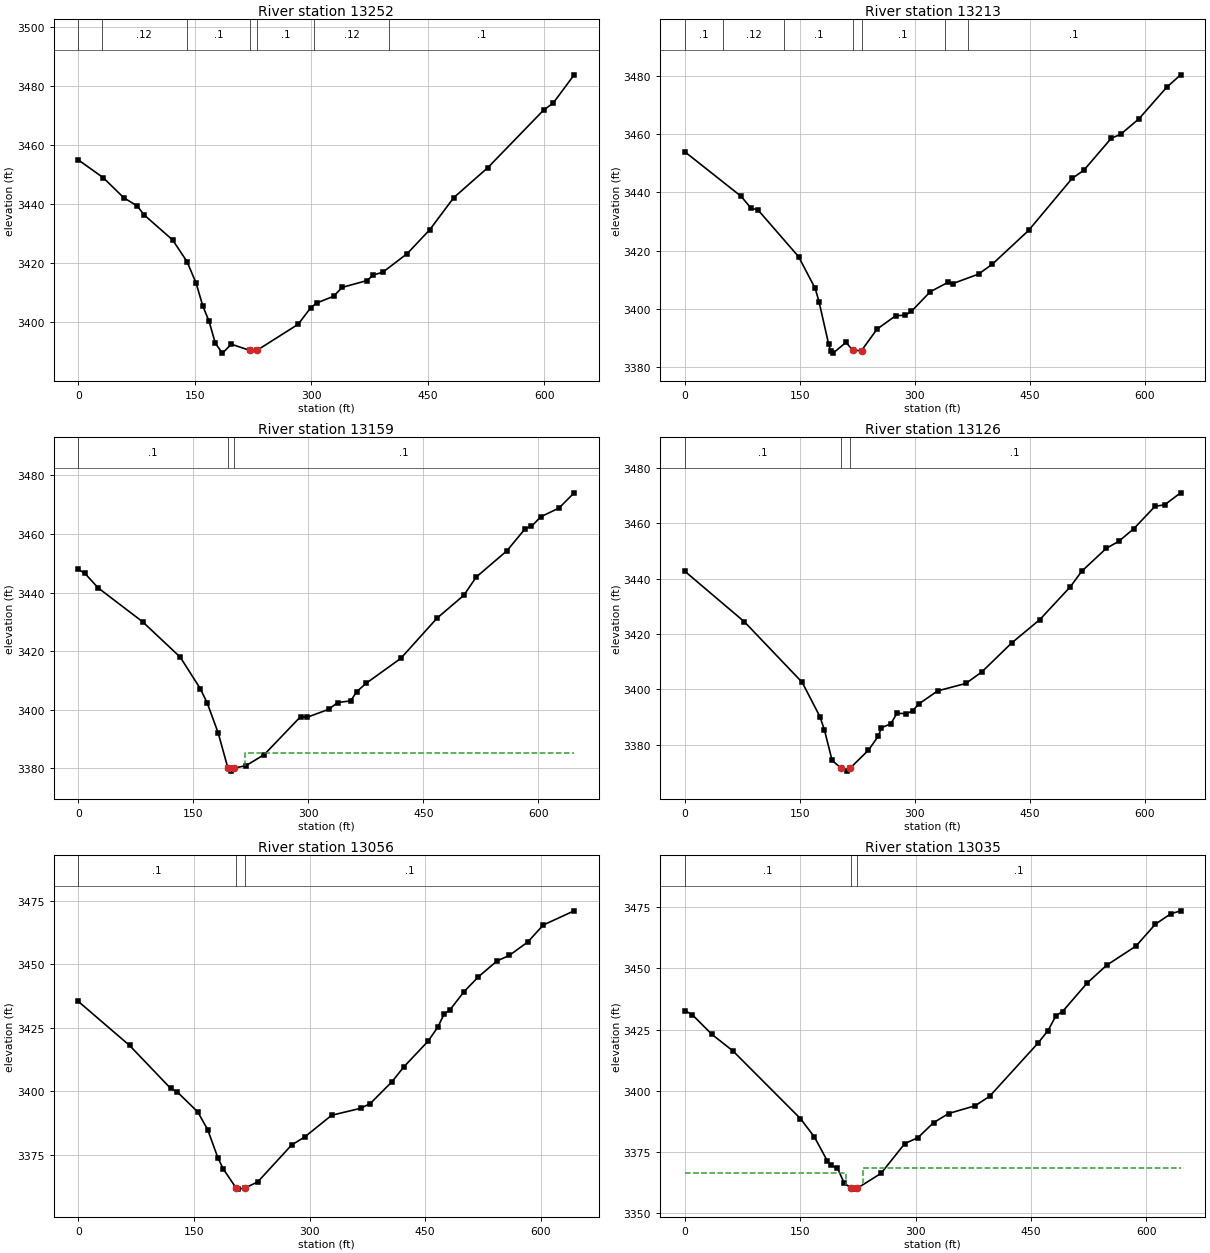
Type RM Length L Ch R = 1 ,13252   ,37,38.6,40.5
XS GIS Cut Line= 6
2319640.13171273659386.1347480772319568.07992596 659234.03672922
2319465.53840223659209.8112797962319418.72946451659214.335839645
2319276.17058672659093.7767886712319145.05161887659094.656781744
#Sta/Elev= 30
       0 3455.05      32 3449.05    58.6 3442.21    75.8 3439.44    84.8 3436.38
   121.4 3427.93     140 3420.55   151.5 3413.39   160.4 3405.45   168.3 3400.37
   176.4 3392.89   185.6 3389.54     197 3392.57   220.8 3390.47   229.9 3390.46
   283.1 3399.33   299.1 3404.87     307 3406.54   328.7 3408.82   339.8 3411.83
   371.6 3414.14   380.1 3416.06   392.1 3416.98   423.6  3423.3   452.6  3431.4
   483.5 3442.28   527.4 3452.46   599.4 3472.01   611.4 3474.29   638.5 3483.91
#Mann= 7 ,-1,0
       0      .1       0      30     .12       0     140      .1       0
   220.8    .045       0   229.9      .1       0  303.67     .12       0
  400.69      .1       0
Bank Sta=220.8,229.9
XS Rating Curve= 0 ,0
Exp/Cntr(USF)=0,0
Exp/Cntr=0.3,0.1

Type RM Length L Ch R = 1 ,13213   ,51.7,54.1,55
XS GIS Cut Line= 6
2319652.39338644659379.7439620712319581.11394754659226.625167403
2319515.11446708659176.4655622542319439.43506282659190.545451419
2319296.87618503659069.9864004452319165.75721718659070.866393517
#Sta/Elev= 30
       0 3453.97    73.4 3438.68    86.4 3434.59    95.5 3433.98   148.4 3417.93
   170.1 3407.01   175.1 3402.39   187.7 3387.78   190.2 3385.58   193.4 3384.81
   210.3 3388.52   219.1 3385.73   230.5  3385.7   250.6 3393.02   275.1 3397.68
   287.3 3397.82   295.5 3399.14   319.9 3405.86   343.3 3409.14   349.5 3408.69
   383.1 3411.96   401.1 3415.38   448.3 3426.94   505.2 3444.86   520.2 3447.57
   556.2 3458.62   568.2 3459.94   592.2 3465.27   628.2 3476.06   646.6  3480.4
#Mann= 7 ,-1,0
       0      .1       0      50     .12       0     130      .1       0
   219.1    .045       0   230.5      .1       0  338.77     .12       0
  368.77      .1       0
Bank Sta=219.1,230.5
XS Rating Curve= 0 ,0
Exp/Cntr(USF)=0,0
Exp/Cntr=0.3,0.1

Type RM Length L Ch R = 1 ,13159   ,32.8,32.9,33.8
XS GIS Cut Line= 6
2319683.11896528659353.6384321672319611.83952638659200.519637499
2319545.84004592659150.3600323492319470.16064166659164.439921514
2319327.60176387659043.8808705412319196.48279602659044.760863613
#Sta/Elev= 30
       0  3447.9     8.6 3446.51    25.9 3441.57    83.8 3430.03   132.9 3417.96
   159.1  3407.2   168.1 3402.32   182.5 3392.01   195.13380.085   198.6 3379.09
   202.4 3380.07   218.7 3380.97   242.4 3384.71   289.9 3397.69   298.2 3397.44
   326.7 3400.18   338.2 3402.49   355.2 3403.04   362.8 3406.12   375.1    3409
   420.5 3417.54   467.6 3431.21   502.8 3439.08   518.9 3445.28   558.9 3454.23
   582.9 3461.82   590.9 3462.53   602.9 3465.81   626.9 3468.82   646.6    3474
#Mann= 3 ,-1,0
       0      .1       0   195.1    .045       0   202.4      .1       0
#XS Ineff= 2 , 0
                          216.82         3385.21
Permanent Ineff=
       F       F
Bank Sta=195.1,202.4
XS Rating Curve= 0 ,0
Exp/Cntr(USF)=0,0
Exp/Cntr=0.3,0.1

Type RM Length L Ch R = 1 ,13126   ,71.6,70.8,71.4
XS GIS Cut Line= 6
2319705.94320033 659330.783088512319634.66376144659177.664293842
2319568.66428098659127.5046886922319492.98487671659141.584577857
2319350.42599892659021.0255268832319219.30703107659021.905519956
#Sta/Elev= 30
       0 3442.68    77.8 3424.39   153.1 3402.55   176.3 3390.13   182.1 3385.36
   192.1 3374.35   203.83371.618     211  3370.5   215.23371.468   239.5 3378.07
   252.3  3383.1   256.4 3386.18   268.6 3387.57   276.7 3391.39   288.9 3391.25
     297 3392.24   305.1 3394.74   329.8 3399.48   366.6 3402.17   387.5 3406.35
   426.1 3416.73     463 3425.21   502.8 3437.07   517.7 3442.68   549.6 3450.93
   565.7 3453.43   585.7 3458.06   613.2 3466.11   625.7 3466.64   646.6 3470.98
#Mann= 3 ,-1,0
       0      .1       0   203.8    .045       0   215.2      .1       0
Bank Sta=203.8,215.2
XS Rating Curve= 0 ,0
Exp/Cntr(USF)=0,0
Exp/Cntr=0.3,0.1

Type RM Length L Ch R = 1 ,13056   ,24.8,20.6,19.3
XS GIS Cut Line= 6
 2319758.7427847659281.5034764332319687.46334581659128.384681765
2319632.40721227659087.9057296662319552.93972638659096.513945368
2319403.22558329658971.7459148062319272.10661544658972.625907879
#Sta/Elev= 30
       0 3435.38    66.5 3418.04   119.8 3401.12   128.3 3399.73   154.8  3391.9
   167.8 3384.88   181.1 3373.73   187.8 3369.47   204.53361.988   207.7 3361.44
   216.5 3361.95   232.6 3364.25   276.7 3378.83   293.8 3382.02   328.6 3390.54
   366.1 3393.28   378.6 3395.14   406.7  3403.7   422.3 3409.63   453.6 3419.69
   466.1 3425.16   474.4 3430.35     482 3432.04   500.4 3439.26   519.1 3445.12
   543.1 3451.33   559.1 3453.53   583.1 3458.83   603.1 3465.49   643.2 3471.09
#Mann= 3 ,-1,0
       0      .1       0   204.5    .045       0   216.5      .1       0
Bank Sta=204.5,216.5
XS Rating Curve= 0 ,0
Exp/Cntr(USF)=0,0
Exp/Cntr=0.3,0.1

Type RM Length L Ch R = 1 ,13035   ,34.8,38.1,45.6
XS GIS Cut Line= 6
2319765.91782152 659266.076528612319684.40861686659084.728298152
2319619.88866948659083.1344568682319556.28058541659088.917009965
2319404.65543207658964.7928219162319283.35101572658963.213337328
#Sta/Elev= 30
       0 3432.76     9.8 3431.04    35.3 3422.98    62.4 3416.28   150.3  3388.5
   168.4 3381.01   185.2 3371.22   189.6 3369.31   198.3 3368.32   207.1 3362.17
   215.9 3360.01   219.1 3359.61   224.1 3359.96   255.1 3366.08   285.9 3378.25
   303.2 3380.73   323.3 3386.82   342.9 3390.59   377.3 3393.75   396.3 3397.66
   459.4 3419.53   472.1 3424.55   482.5 3430.66     491 3432.36   523.2 3444.11
   548.4 3451.33   586.5 3459.19   611.7 3468.16   631.7  3472.4   644.5 3473.62
#Mann= 3 ,-1,0
       0      .1       0   215.9    .045       0   224.1      .1       0
#XS Ineff= 2 , 0
          210.05 3366.03  232.26         3368.17
Permanent Ineff=
       F       F
Bank Sta=215.9,224.1
XS Rating Curve= 0 ,0
Exp/Cntr(USF)=0,0
Exp/Cntr=0.3,0.1

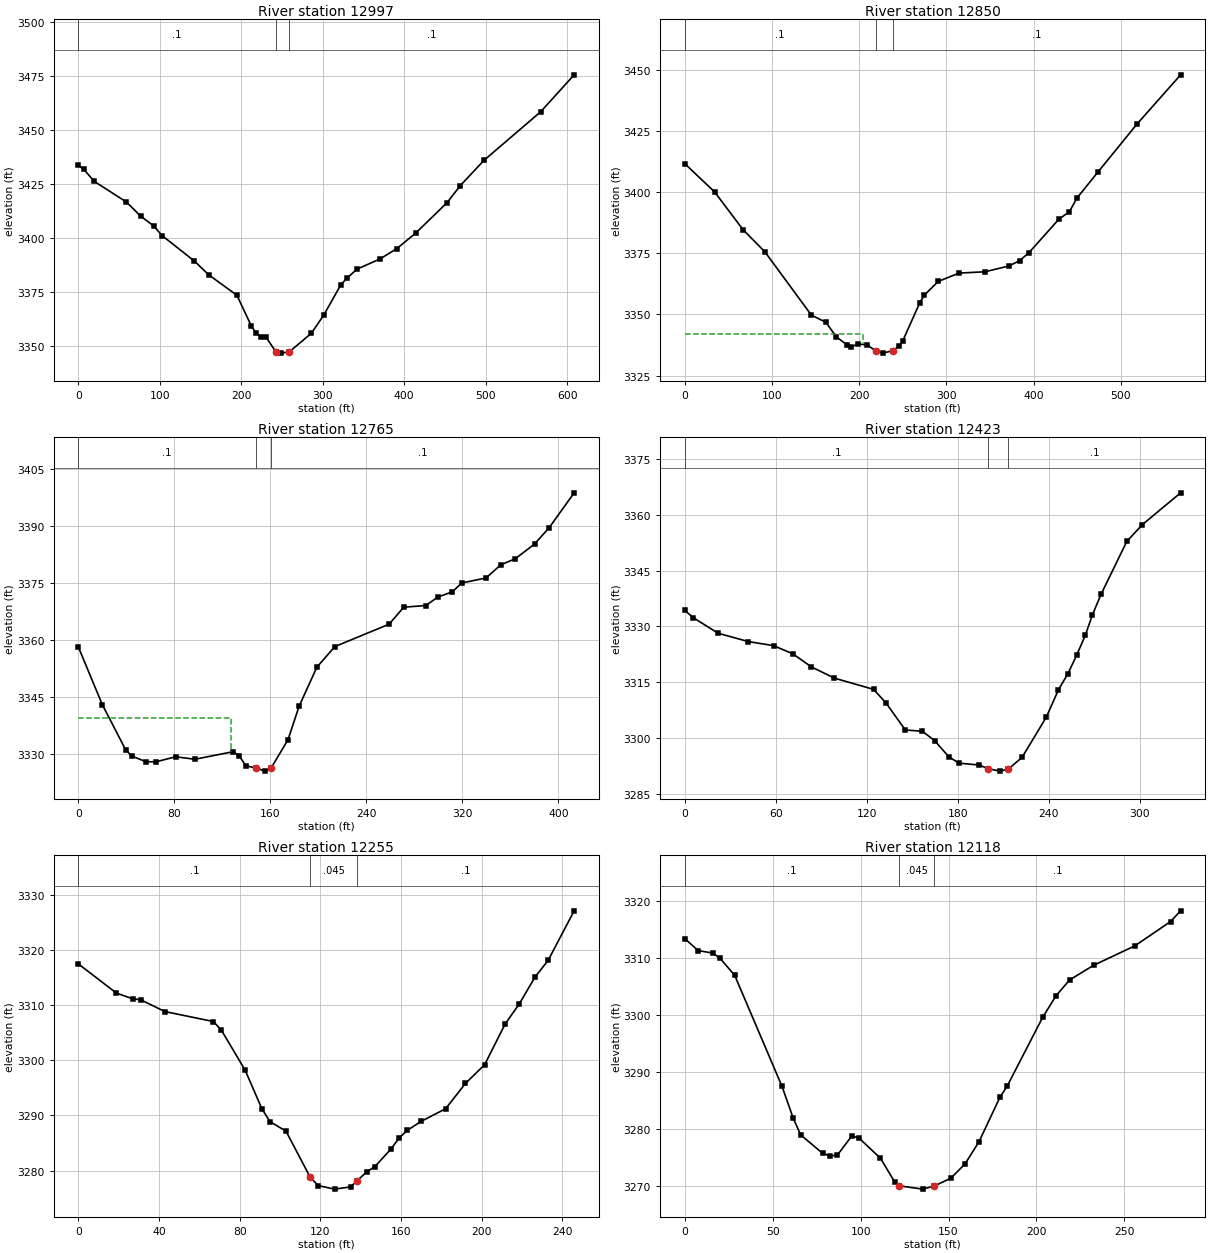
Type RM Length L Ch R = 1 ,12997   ,145.7,146.8,149
XS GIS Cut Line= 6
2319780.05607274659258.9777367912319695.08785271659071.636989292
2319640.03171918659031.1580371932319560.56423329659039.766252894
 2319410.8500902658914.9982223332319351.01056125658913.238236188
#Sta/Elev= 30
       0 3433.81     6.4  3432.1    19.5 3426.39    59.1  3416.8    76.6 3410.24
    92.3 3405.81     103  3401.2   142.5 3389.45   160.1 3383.07   194.7 3373.61
   212.4 3359.35   218.1 3356.13   223.9 3354.46   230.1 3354.37   242.7 3347.31
     249  3346.8     259 3347.39     286 3355.97   301.2 3364.35   322.2 3378.43
   330.2 3381.68   342.3 3385.74   370.1 3390.39   390.9  3395.2   414.3 3402.47
   452.7 3416.53     469 3424.46   498.1 3436.16   567.5  3458.6   608.7 3475.75
#Mann= 3 ,-1,0
       0      .1       0   242.7    .045       0     259      .1       0
Bank Sta=242.7,259
XS Rating Curve= 0 ,0
Exp/Cntr(USF)=0,0
Exp/Cntr=0.3,0.1

Type RM Length L Ch R = 1 ,12850   ,84.7,84.9,84.5
XS GIS Cut Line= 4
2319842.92004011659170.6466721222319800.15237677658984.607336601
 2319740.2776481658915.4662808712319458.72386445658864.145084865
#Sta/Elev= 30
       0 3411.68    34.3 3400.07    66.9 3384.62    91.8 3375.64   145.2 3349.69
   161.6 3346.83   173.9 3340.78   186.2  3337.5   190.3 3336.69     199 3337.93
   209.2  3337.5   218.8  3335.1   227.5 3334.17   238.7 3335.23   245.9 3337.12
     250 3339.28   269.5 3354.84   274.8 3357.95   290.6 3363.51   314.4 3366.91
   344.3 3367.46   371.9 3369.86   384.1 3372.05   394.5 3375.21   428.8 3388.94
     441 3392.03   449.5 3397.56   473.6 3408.22   518.3 3427.82   568.5 3448.03
#Mann= 3 ,-1,0
       0      .1       0   218.8    .045       0   238.7      .1       0
#XS Ineff= 2 , 0
          204.04 3342.16
Permanent Ineff=
       F       F
Bank Sta=218.8,238.7
XS Rating Curve= 0 ,0
Exp/Cntr(USF)=0,0
Exp/Cntr=0.3,0.1

Type RM Length L Ch R = 1 ,12765   ,339.2,341.8,339.8
XS GIS Cut Line= 4
2319886.25766754 659044.827687922319865.36346841658930.327476675
2319773.42899222 658828.363784912319615.46884678658806.633817812
#Sta/Elev= 30
       0 3358.19      20 3342.96    39.3 3331.14    44.4 3329.42    56.5 3327.91
    64.7  3327.9      81 3329.22    97.2 3328.57   128.7 3330.55   134.1 3329.46
   139.5 3326.85     148 3326.27   155.6 3325.44   160.5 3326.21   174.7 3333.72
   183.9 3342.52   198.7 3352.83   213.7 3358.28     259  3364.2   271.1 3368.67
   289.6 3369.11   299.4 3371.33   311.5 3372.71   319.5 3375.06   339.7 3376.38
   351.9 3379.83     364 3381.44   380.1 3385.33   392.2  3389.6   413.1 3398.83
#Mann= 3 ,-1,0
       0      .1       0     148    .045       0   160.5      .1       0
#XS Ineff= 2 , 0
           127.5 3339.41
Permanent Ineff=
       F       F
Bank Sta=148,160.5
XS Rating Curve= 0 ,0
Exp/Cntr(USF)=0,0
Exp/Cntr=0.3,0.1

Type RM Length L Ch R = 1 ,12423   ,163.4,168.5,172.4
XS GIS Cut Line= 4
 2320140.7033792658926.6137201512320109.52575262658787.873281898
2320048.20975369658695.8992835052319995.72741563658643.416945439
#Sta/Elev= 30
       0 3334.29     5.6 3332.32      22 3328.15    41.8 3325.92    58.6 3324.81
    71.2 3322.63    83.5 3319.11    98.7 3316.08   124.5 3313.07   132.7 3309.42
   145.4 3302.16   156.7  3301.8   164.7 3299.32     174 3295.01   180.7 3293.25
   194.2 3292.74   199.9 3291.76   207.9  3291.1   213.43291.669   222.4 3294.77
   238.4 3305.59   246.4 3312.93   252.7 3317.32   258.4 3322.21   264.1 3327.56
   268.8 3333.06   274.5  3338.6   291.5 3352.82   301.8 3357.35     327 3365.88
#Mann= 3 ,-1,0
       0      .1       0   199.9    .045       0   213.4      .1       0
Bank Sta=199.9,213.4
XS Rating Curve= 0 ,0
Exp/Cntr(USF)=0,0
Exp/Cntr=0.3,0.1

Type RM Length L Ch R = 1 ,12255   ,138,137.3,136.1
XS GIS Cut Line= 3
2320232.33494706658856.0713536362320240.69262671658690.589296509
2320193.88962066658625.399395216
#Sta/Elev= 30
       0 3317.44    18.9 3312.15    26.9 3311.13    30.9 3310.95    42.9 3308.81
      67    3307      71  3305.4    82.7 3298.21      91 3291.23      95 3288.89
     103 3287.14     115  3278.8     119 3277.29   127.1 3276.65   135.1 3277.06
   138.2 3278.15   143.1  3279.8   147.1 3280.74   155.1 3283.93   159.1 3285.93
   163.1 3287.28   169.9  3288.9   182.2 3291.22     192  3295.8   201.5 3299.18
   211.7 3306.57   218.7  3310.2   226.5 3315.06     233 3318.08   245.9 3327.05
#Mann= 3 ,-1,0
       0      .1       0     115    .045       0   138.2      .1       0
Bank Sta=115,138.2
XS Rating Curve= 0 ,0
Exp/Cntr(USF)=0,0
Exp/Cntr=0.3,0.1

Type RM Length L Ch R = 1 ,12118   ,270.4,259.9,256.5
XS GIS Cut Line= 4
2320348.72971124658864.4382407882320376.88948957658767.639002779
2320370.72953806658628.6000972762320348.80495065658592.782443228
#Sta/Elev= 30
       0 3313.46     7.6 3311.36    15.9 3310.93    20.1 3309.99    28.4    3307
    55.3 3287.48    61.7 3281.87    65.9 3278.97    78.4 3275.72    82.5 3275.26
    86.7 3275.39      95 3278.78      99 3278.43   111.3 3274.85   119.3 3270.73
     1223270.013   135.3 3269.43   141.8 3269.97   151.3 3271.35   159.3 3273.83
   167.3 3277.74   179.3 3285.62   183.4 3287.56   203.5 3299.61   211.2 3303.45
   218.9 3306.21   232.5 3308.77     256  3312.2   276.3 3316.47     282 3318.35
#Mann= 3 ,-1,0
       0      .1       0     122    .045       0   141.8      .1       0
Bank Sta=122,141.8
XS Rating Curve= 0 ,0
Exp/Cntr(USF)=0,0
Exp/Cntr=0.3,0.1

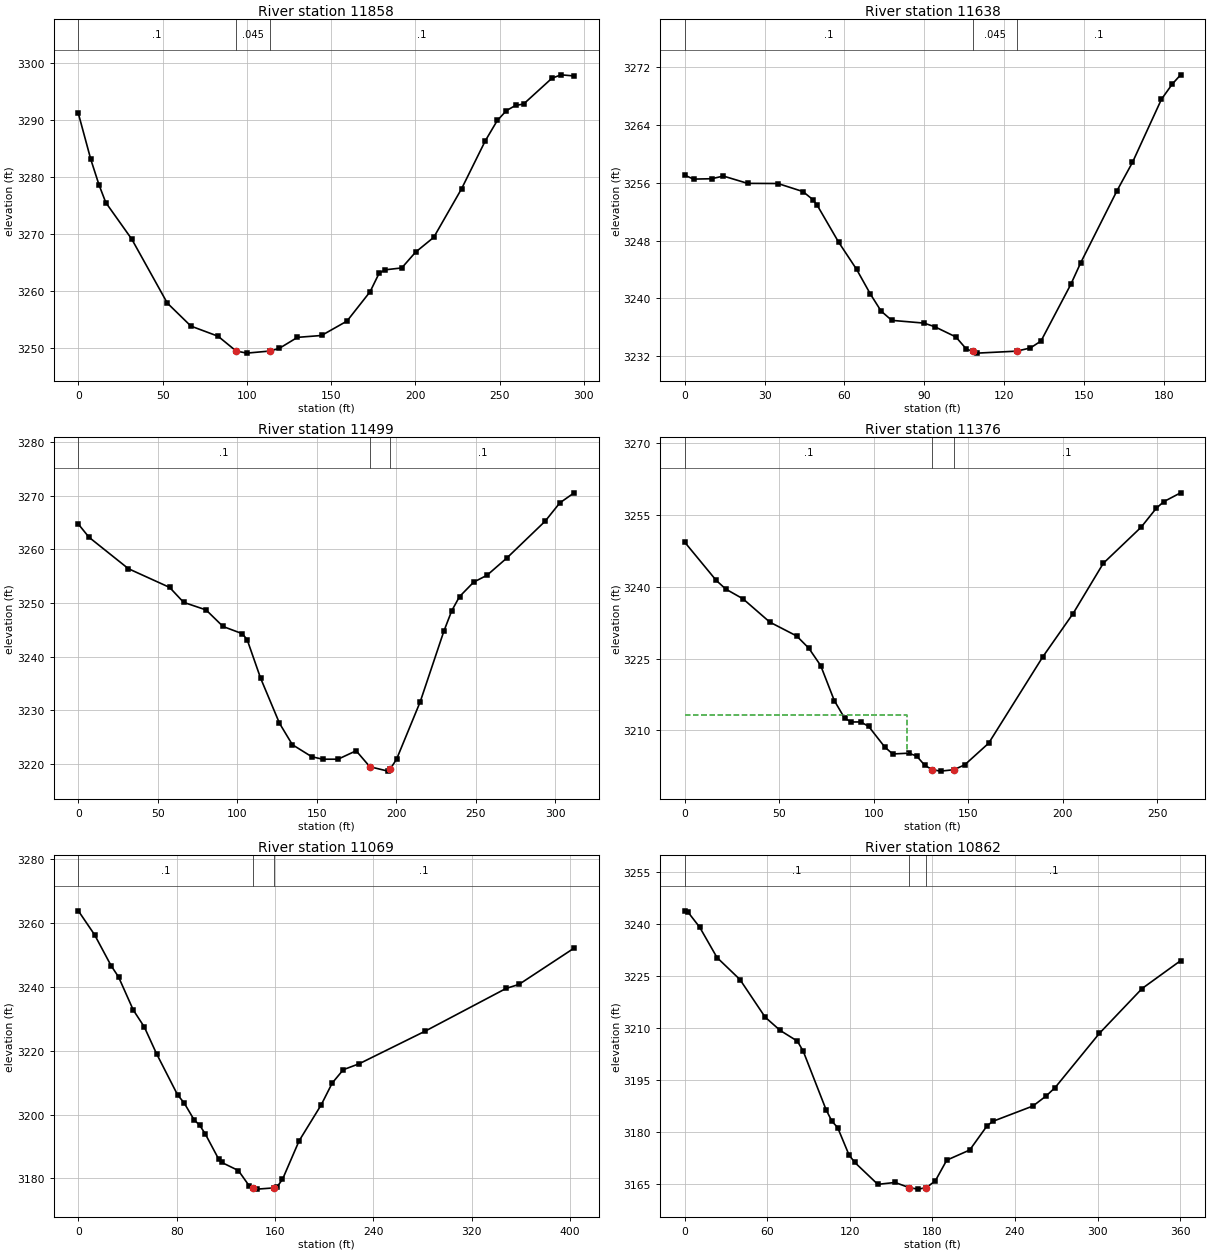
Type RM Length L Ch R = 1 ,11858   ,214.1,220,226.2
XS GIS Cut Line= 3
2320652.69580086658905.2535250962320641.72589521658841.743545038
2320487.56985271658671.421325792
#Sta/Elev= 30
       0 3291.16     7.4 3283.06    12.3 3278.57    16.3 3275.48    31.7 3269.06
    52.8 3257.82    66.8 3253.78    82.9    3252    93.6 3249.41    99.9 3249.03
   113.8  3249.4   119.2 3249.86     130  3251.8   144.3 3252.13   159.4 3254.66
   173.1 3259.81   178.5 3263.08   182.1 3263.67   191.9    3264   200.1 3266.77
   210.9 3269.38   227.4 3277.91   241.5 3286.35   248.6 3289.91     254 3291.64
   259.4 3292.55   264.2  3292.8     281 3297.33   286.4 3297.93   294.2 3297.73
#Mann= 3 ,-1,0
       0      .1       0    93.6    .045       0   113.8      .1       0
Bank Sta=93.6,113.8
XS Rating Curve= 0 ,0
Exp/Cntr(USF)=0,0
Exp/Cntr=0.3,0.1

Type RM Length L Ch R = 1 ,11638   ,135.1,138.6,143.4
XS GIS Cut Line= 4
2320705.80865034658776.2413082772320740.90830785658741.921643158
2320744.02827741658645.9825793032320732.71838777 658606.20296746
#Sta/Elev= 30
       0 3257.02     3.3 3256.49    10.1 3256.54    14.5 3256.91    23.6  3255.9
      35 3255.88    44.4 3254.77    48.1 3253.67    49.8 3252.86    57.8 3247.79
    64.6 3244.01    69.8 3240.58    73.8 3238.25    77.8 3236.97    89.9 3236.59
    93.9  3236.1   101.9 3234.68   105.9 3232.98   108.5 3232.67   109.9 3232.44
   124.73232.712   129.9 3233.15   133.9 3234.11   145.1 3241.93   148.8  3244.9
   162.5  3254.9   168.3  3258.8   179.2 3267.53   183.3 3269.64   186.4  3270.9
#Mann= 3 ,-1,0
       0      .1       0   108.5    .045       0   124.7      .1       0
Bank Sta=108.5,124.7
XS Rating Curve= 0 ,0
Exp/Cntr(USF)=0,0
Exp/Cntr=0.3,0.1

Type RM Length L Ch R = 1 ,11499   ,124.7,123.1,121.1
XS GIS Cut Line= 3
2320761.40882508658858.600340344 2320905.1723254 658662.29676562
2320886.11933138658596.477331742
#Sta/Elev= 30
       0  3264.7     6.7 3262.25    31.5 3256.39    57.4 3252.91    66.2 3250.13
    80.3 3248.72      91 3245.63   103.2 3244.28   106.2 3243.15   114.6 3236.02
   126.5 3227.61   134.6 3223.62   146.8 3221.38   153.6 3220.92   163.3 3220.92
   174.7 3222.49   183.3 3219.52   194.7  3218.7   196.33219.185   200.1  3220.9
     215 3231.62   229.8  3244.7   234.8 3248.55   239.7 3251.19   248.6 3253.89
     257 3255.17   269.5 3258.39   293.5 3265.22   302.8 3268.65   311.8 3270.52
#Mann= 3 ,-1,0
       0      .1       0   183.3    .045       0   196.3      .1       0
Bank Sta=183.3,196.3
XS Rating Curve= 0 ,0
Exp/Cntr(USF)=0,0
Exp/Cntr=0.3,0.1

Type RM Length L Ch R = 1 ,11376   ,301.8,307,311.3
XS GIS Cut Line= 4
2320910.36859649658874.766517086 2320962.9086709658811.256537028
2320992.93157057658724.0746553122320994.66366093658636.315410142
#Sta/Elev= 30
       0  3249.3    16.6 3241.35    21.7 3239.52    30.8 3237.49      45 3232.62
    59.2 3229.73    65.6 3227.19    71.9 3223.56    79.1 3216.25    84.6 3212.54
    88.2 3211.76    93.1 3211.78    97.3 3210.84   105.8 3206.55     110 3205.08
   118.5 3205.25   122.7 3204.65   126.9 3202.76   130.93201.792   135.4  3201.5
   142.3 3201.79   148.1  3202.8   160.8 3207.33   189.5  3225.4   205.5 3234.42
   221.5 3244.92   241.5 3252.45   249.5  3256.4   253.5 3257.79   262.4 3259.63
#Mann= 3 ,-1,0
       0      .1       0   130.9    .045       0   142.3      .1       0
#XS Ineff= 2 , 0
          117.49 3213.28
Permanent Ineff=
       F       F
Bank Sta=130.9,142.3
XS Rating Curve= 0 ,0
Exp/Cntr(USF)=0,0
Exp/Cntr=0.3,0.1

Type RM Length L Ch R = 1 ,11069   ,204.2,206.7,205.8
XS GIS Cut Line= 3
2321036.45635491659053.4522573172321233.96591126658951.764168904
2321358.14271153658819.765207982
#Sta/Elev= 30
       0 3263.85    13.2 3256.36    26.7 3246.63    32.7 3243.14    44.7 3232.76
    53.7 3227.43    63.6 3219.09    80.7  3206.2    86.1 3203.62    94.2 3198.34
    98.7 3196.66   103.2 3193.98   114.2 3186.01   116.7 3184.98   130.2 3182.45
   139.2 3177.55   141.83176.946   145.5 3176.62   159.23177.006   161.6 3177.29
   166.1 3179.68   179.6 3191.74   197.6 3203.03   206.6  3209.9   215.6 3214.06
   228.4  3215.9   282.1 3226.12     348 3239.52   358.5 3240.79   403.4 3252.17
#Mann= 3 ,-1,0
       0      .1       0   141.8    .045       0   159.2      .1       0
Bank Sta=141.8,159.2
XS Rating Curve= 0 ,0
Exp/Cntr(USF)=0,0
Exp/Cntr=0.3,0.1

Type RM Length L Ch R = 1 ,10862   ,175,175.9,176.1
XS GIS Cut Line= 2
2321109.78911098659205.9843899382321454.94194954659102.340761362
#Sta/Elev= 30
       0 3243.78     2.5 3243.31    10.8 3239.08    23.4 3230.34    40.1 3223.99
    58.4 3213.17    69.3 3209.35    81.8 3206.27    86.1 3203.35   102.7 3186.51
   106.9 3183.22   111.1 3181.37   119.4 3173.46   123.6 3171.32   140.3 3165.02
   152.8 3165.57   163.2 3164.07   169.5 3163.65   175.5 3164.06   182.1 3166.03
   190.4 3171.99   207.1 3174.91   219.7 3181.87   223.8 3183.15   253.1 3187.59
   262.7 3190.49   269.2  3192.9   301.3 3208.48   332.4 3221.41   360.4 3229.43
#Mann= 3 ,-1,0
       0      .1       0   163.2    .045       0   175.5      .1       0
Bank Sta=163.2,175.5
XS Rating Curve= 0 ,0
Exp/Cntr(USF)=0,0
Exp/Cntr=0.3,0.1