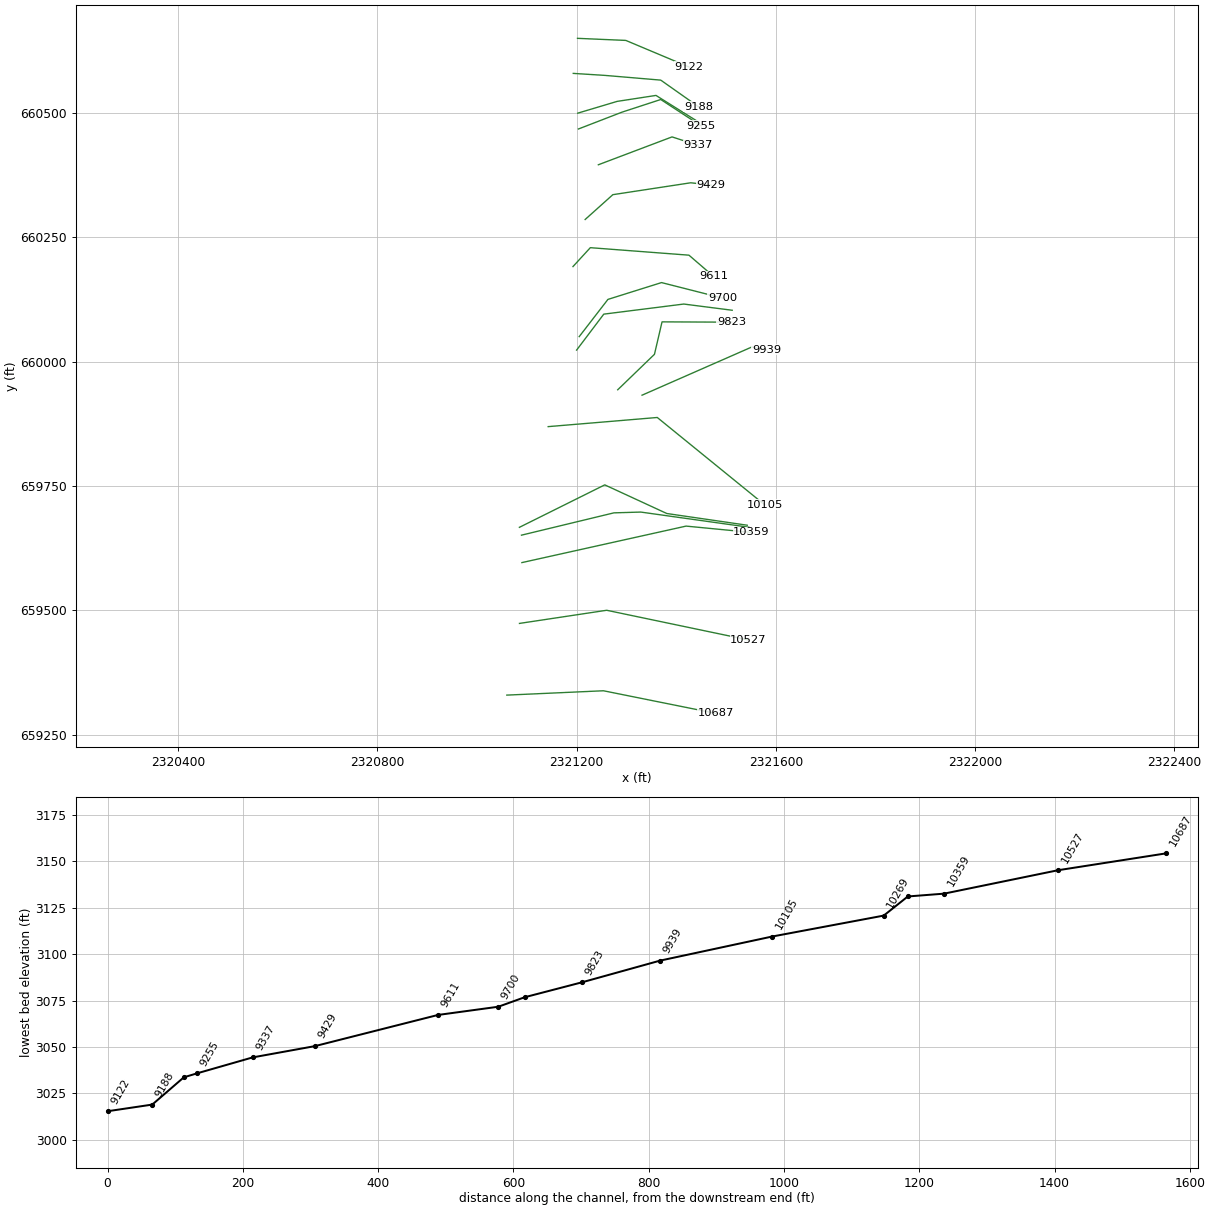
HEC-RAS study FISHHAWKCK.prj: FISHHAWKCK

--- FISHHAWKCK.g01 (geometry) --- (continued)

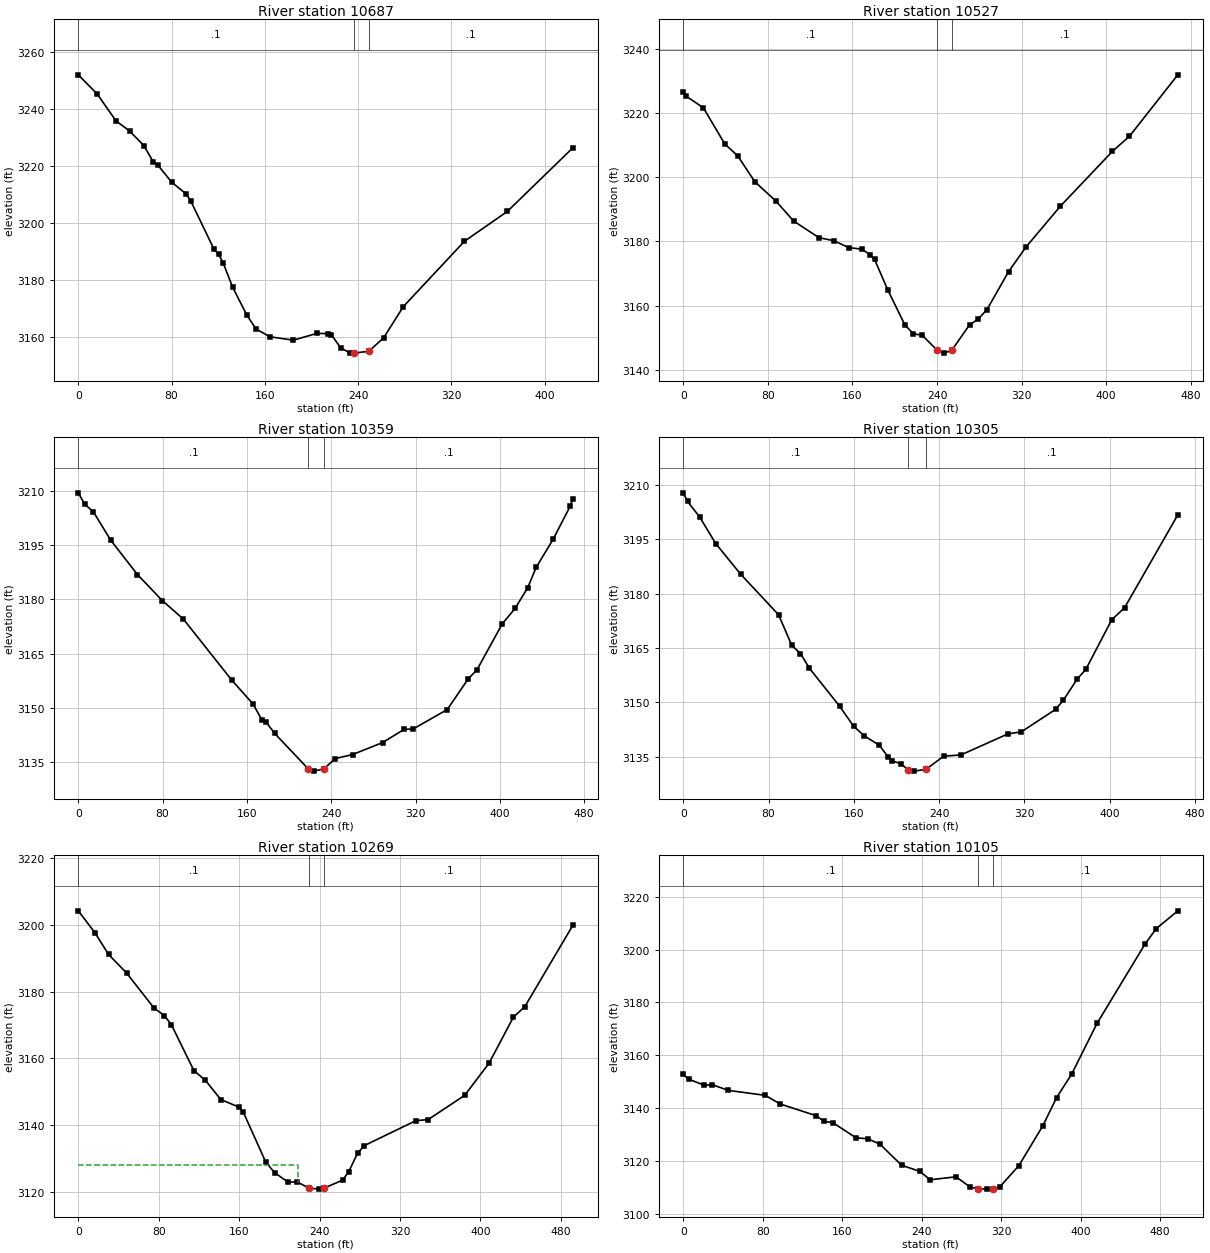
Type RM Length L Ch R = 1 ,10687   ,159.5,159.4,159.4
XS GIS Cut Line= 3
2321059.91346683 659329.805973322321253.87300148659338.542889295
2321479.28543364659293.110926224
#Sta/Elev= 30
       0 3251.89    16.3 3245.12    32.3 3235.76    44.3 3232.07    56.3 3227.02
    64.3 3221.37    68.3 3220.17    80.3 3214.13    92.4 3210.15    96.4 3207.68
   116.4  3190.7   120.4 3188.86   124.4 3185.72   132.4 3177.36   144.4  3167.7
   152.4 3162.71   164.4 3159.97   184.4 3158.78   204.7 3161.16   214.2 3161.08
   216.9 3160.76   225.1 3156.08   233.2 3154.23   236.13154.251   249.13154.856
   261.8 3159.56   278.8 3170.57   331.2 3193.49   367.9 3203.93   424.1 3226.25
#Mann= 3 ,-1,0
       0      .1       0   236.1    .045       0   249.1      .1       0
Bank Sta=236.1,249.1
XS Rating Curve= 0 ,0
Exp/Cntr(USF)=0,0
Exp/Cntr=0.3,0.1

Type RM Length L Ch R = 1 ,10527   ,164.6,168.5,170.6
XS GIS Cut Line= 3
2321085.34485896659473.8933921042321260.36570344659500.293184288
2321544.89679698659440.649209353
#Sta/Elev= 30
       0 3226.48     2.9 3225.25      19 3221.66    39.3 3210.36    51.4 3206.72
    67.6 3198.64    87.8 3192.51   104.3 3186.37   128.3 3181.18   142.5 3180.21
   156.5 3178.06   168.7 3177.61   176.8 3175.87   180.9 3174.38   193.4 3164.87
   209.5 3154.01   217.7 3151.16   225.8  3150.8   240.3 3145.99   246.3 3145.17
   253.8    3146   270.8 3154.03     279 3155.81   287.2 3158.76   307.6 3170.56
   323.9 3178.17   356.6 3190.98   405.8 3208.07     422 3212.81   467.7 3231.95
#Mann= 3 ,-1,0
       0      .1       0   240.3    .045       0   253.8      .1       0
Bank Sta=240.3,253.8
XS Rating Curve= 0 ,0
Exp/Cntr(USF)=0,0
Exp/Cntr=0.3,0.1

Type RM Length L Ch R = 1 ,10359   ,54,53.5,50.9
XS GIS Cut Line= 3
2321090.23370936659596.1146522162321419.74222663659669.447408284
2321550.76341747659656.736397232
#Sta/Elev= 30
       0 3209.43     6.1 3206.29    14.3  3204.2    30.7 3196.39    56.1 3186.87
    79.8 3179.65    99.7 3174.56   145.4 3157.78   165.9 3151.07   174.1 3146.78
   178.2  3146.1   186.4 3142.96   218.23133.184   223.7 3132.56   233.1  3133.2
   243.8 3136.03   260.2 3137.13   288.8 3140.46   309.3 3144.12   317.6 3144.18
   350.1 3149.57   370.2 3158.14   378.2 3160.49   402.3 3173.25   414.4 3177.49
   426.4  3183.2   434.5 3188.86   450.5 3196.57   466.6 3205.66   469.2  3207.7
#Mann= 3 ,-1,0
       0      .1       0   218.2    .045       0   233.1      .1       0
Bank Sta=218.2,233.1
XS Rating Curve= 0 ,0
Exp/Cntr(USF)=0,0
Exp/Cntr=0.3,0.1

Type RM Length L Ch R = 1 ,10305   ,40.6,35.6,33.9
XS GIS Cut Line= 4
2321089.30143338659651.2289976442321274.93962198659696.078560015
2321328.75909683659697.6385447932321545.59698099 659667.21884162
#Sta/Elev= 30
       0 3207.84       4 3205.45    15.3  3201.2    30.5  3193.8    53.7 3185.42
    89.4 3174.18   101.7 3165.76   109.9  3163.5   118.2 3159.46   146.5    3149
   159.8 3143.41   169.7  3140.8     184 3138.16   192.2 3134.91   196.2 3133.89
   204.2 3133.06   210.63131.495   216.6 3131.05   227.73131.546   244.2 3135.18
   260.4 3135.52   304.8 3141.37   316.9 3141.86   349.2  3148.1   356.4 3150.59
   369.4 3156.45   377.5 3159.11   401.8  3172.8   413.9 3176.15   463.8 3201.76
#Mann= 3 ,-1,0
       0      .1       0   210.6    .045       0   227.7      .1       0
Bank Sta=210.6,227.7
XS Rating Curve= 0 ,0
Exp/Cntr(USF)=0,0
Exp/Cntr=0.3,0.1

Type RM Length L Ch R = 1 ,10269   ,168.8,164.9,165.1
XS GIS Cut Line= 4
2321085.20334724659666.9983442062321256.48967588659752.290511951
2321381.09346003659694.7270736382321542.55188457659671.210303107
#Sta/Elev= 30
       0 3204.28    16.7 3197.66    30.1  3191.2      48 3185.64    75.4 3175.07
    85.7 3172.83    92.7 3170.05     115 3156.32   126.4 3153.41   141.8 3147.63
   159.7 3145.37   164.2  3143.8   186.5 3128.84   195.4 3125.67   208.6 3122.86
   217.6 3122.91   229.33121.088   239.5 3120.75   244.7 3121.09   262.8 3123.43
   268.8 3125.89   277.8 3131.56   284.6 3133.83   335.8 3141.31   347.9 3141.61
   384.3 3148.91   408.5 3158.54   432.8  3172.4     444 3175.47   491.8 3199.91
#Mann= 3 ,-1,0
       0      .1       0   229.3    .045       0   244.7      .1       0
#XS Ineff= 2 , 0
          218.77 3128.14
Permanent Ineff=
       F       F
Bank Sta=229.3,244.7
XS Rating Curve= 0 ,0
Exp/Cntr(USF)=0,0
Exp/Cntr=0.3,0.1

Type RM Length L Ch R = 1 ,10105   ,157.2,165.8,173.8
XS GIS Cut Line= 3
2321142.93471555659869.3284984052321361.90592246659887.715393642
 2321577.5340575659712.204120931
#Sta/Elev= 30
       0  3152.8     5.3 3151.04    21.3  3148.7    29.3 3148.92    45.4 3146.78
    82.5 3144.92    97.6 3141.64   133.7 3137.22   141.7 3135.09   150.5 3134.61
   173.8 3128.88   185.9 3128.49   197.9 3126.48   219.7 3118.52   238.1 3116.18
   248.5 3113.02   274.5 3114.14   288.6 3110.31   296.23109.611   306.1 3109.48
   312.1 3109.53   318.8  3110.4   337.8 3118.37   361.9 3133.39   375.8 3144.08
   390.9 3152.92   416.5 3172.11   464.8 3202.09   476.2 3207.95   497.8 3214.63
#Mann= 3 ,-1,0
       0      .1       0   296.2    .045       0   312.1      .1       0
Bank Sta=296.2,312.1
XS Rating Curve= 0 ,0
Exp/Cntr(USF)=0,0
Exp/Cntr=0.3,0.1

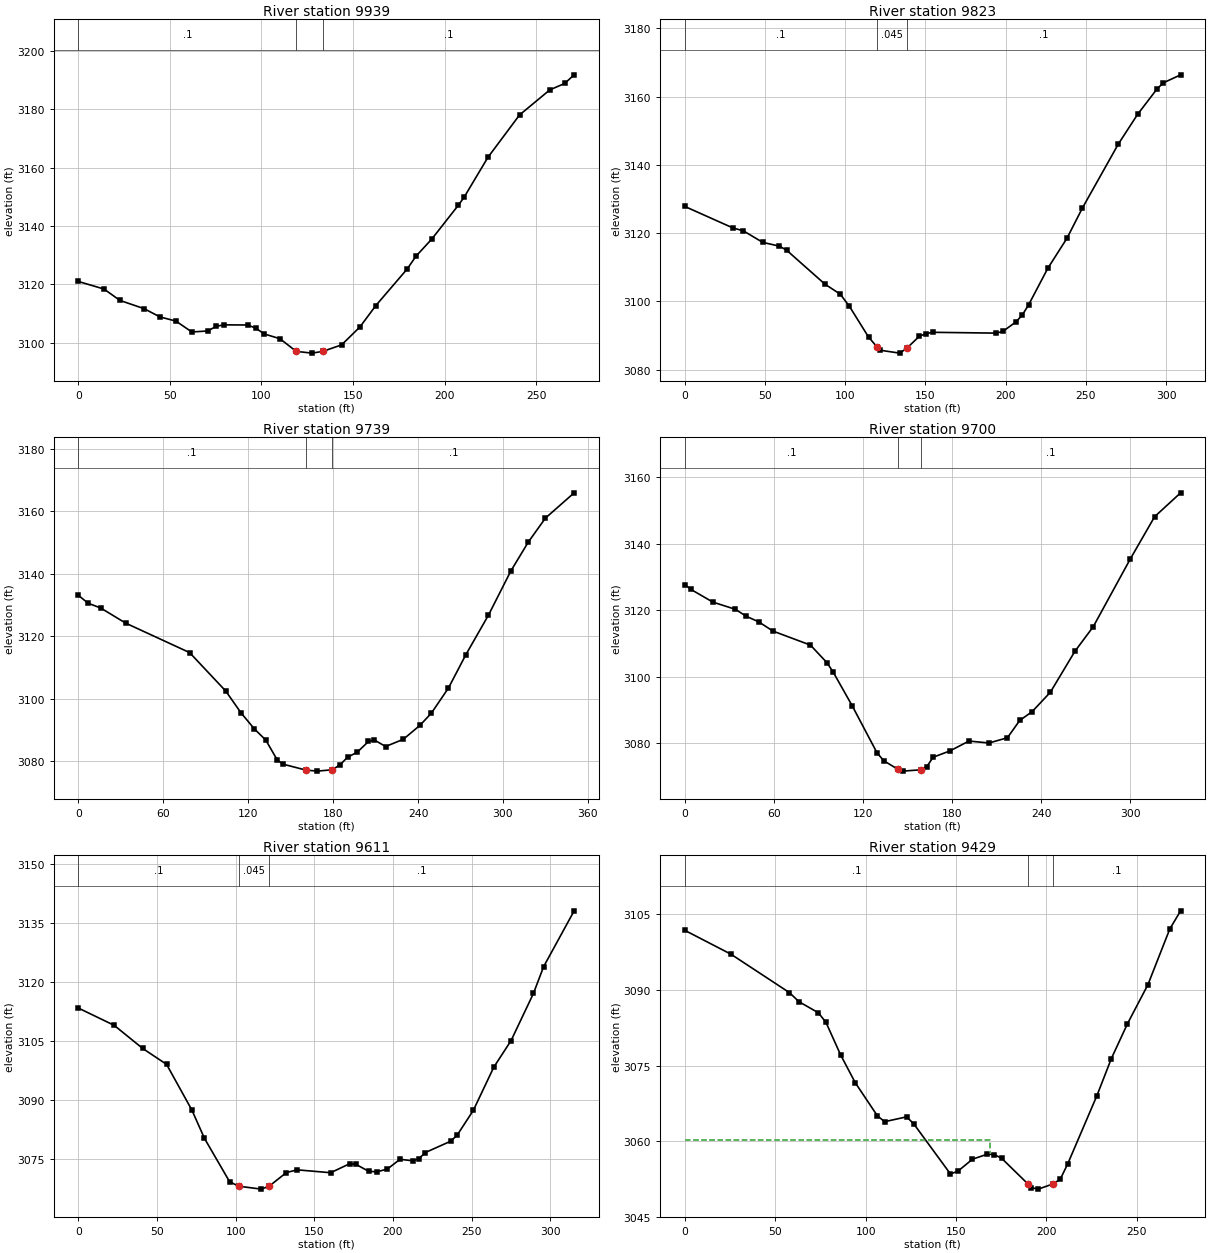
Type RM Length L Ch R = 1 ,9939    ,107.4,115.4,121.9
XS GIS Cut Line= 3
2321331.36982141 659932.540492932321552.01256425660029.489576903
2321581.26444304660023.639201146
#Sta/Elev= 30
       0 3121.03      14 3118.45    22.7 3114.55    35.8 3111.75    44.6  3108.9
    53.3 3107.47      62 3103.74    70.8 3104.09    75.2 3105.67    79.5 3106.18
    92.6 3106.13      97    3105   101.6 3103.05   110.1 3101.44     1193097.103
   127.6  3096.5   133.53097.094   143.8 3099.33   153.8 3105.46   162.5  3112.8
   179.6  3125.3   184.4 3129.67   193.1  3135.6   207.5 3147.09   210.8 3149.98
   223.7 3163.53     241 3178.06   257.5 3186.62   265.6 3188.83   270.8 3191.78
#Mann= 3 ,-1,0
       0      .1       0     119    .045       0   133.5      .1       0
Bank Sta=119,133.5
XS Rating Curve= 0 ,0
Exp/Cntr(USF)=0,0
Exp/Cntr=0.3,0.1

Type RM Length L Ch R = 1 ,9823    ,93.6,84.8,70.5
XS GIS Cut Line= 4
2321282.54557531659943.3909124172321356.26783176660014.676069481
2321371.49970293660079.8684780772321511.02364282660079.259203231
#Sta/Elev= 30
       0  3127.8    30.1 3121.48    36.4 3120.68    48.6 3117.27      59 3116.17
    63.5 3114.96    87.3 3105.05    96.9 3102.09   102.6 3098.53   114.5 3089.55
   119.7 3086.69   121.6 3085.69   133.9 3084.83   138.2  3086.2   146.2 3089.78
   150.3 3090.53   154.4 3090.93   194.2 3090.69   198.2 3091.19   206.2 3093.91
   210.2 3095.91   214.2 3098.92   226.2 3109.66   238.2 3118.51   247.8 3127.35
   270.2  3146.1   282.2 3154.79   294.2 3162.17   298.2 3164.01     309 3166.36
#Mann= 3 ,-1,0
       0      .1       0   119.7    .045       0   138.2      .1       0
Bank Sta=119.7,138.2
XS Rating Curve= 0 ,0
Exp/Cntr(USF)=0,0
Exp/Cntr=0.3,0.1

Type RM Length L Ch R = 1 ,9739    ,38.6,38.9,42.3
XS GIS Cut Line= 4
2321200.01665349660023.1764868082321254.57749999660095.404655037
2321415.14227685 660115.670112312321512.31254633660103.199061681
#Sta/Elev= 30
       0 3133.06     6.9 3130.52    15.8 3128.99    33.4 3124.16    78.6 3114.72
   104.2 3102.38     115 3095.39   124.4 3090.28   132.4 3086.74   140.5 3080.39
   144.5 3079.02   160.7 3077.12   168.8 3076.78   179.5 3077.22   184.9 3078.81
   190.2 3081.23     197 3082.82     205 3086.27     209 3086.78   217.1 3084.66
   229.6 3086.97   241.3 3091.41   249.4 3095.32   261.5 3103.39   273.8 3114.06
   289.7 3126.66   305.5 3140.78   317.9 3150.09     330 3157.76   350.3 3165.85
#Mann= 3 ,-1,0
       0      .1       0   160.7    .045       0   179.5      .1       0
Bank Sta=160.7,179.5
XS Rating Curve= 0 ,0
Exp/Cntr(USF)=0,0
Exp/Cntr=0.3,0.1

Type RM Length L Ch R = 1 ,9700    ,92.7,89.1,85.2
XS GIS Cut Line= 4
2321205.21292458660050.1970965052321262.89153374660125.023400282
2321370.45434542660158.7991624042321493.08634328 660127.62153583
#Sta/Elev= 30
       0 3127.75     4.2 3126.28    18.9 3122.48    34.1 3120.31    41.3 3118.24
    49.9 3116.52    59.3 3113.78    84.6 3109.56    95.8 3104.22     100 3101.36
   112.6  3091.4   129.4 3077.19   133.9 3074.82   143.5 3072.22   146.7 3071.68
   159.33072.091   162.9 3072.98   167.1 3075.84   178.6 3077.78   191.3 3080.72
   204.8 3080.14   217.2 3081.71   225.5 3086.93   233.8 3089.54   246.1 3095.39
   262.6 3107.68     275 3115.11   299.8 3135.36   316.3 3148.16   333.8 3155.33
#Mann= 3 ,-1,0
       0      .1       0   143.5    .045       0   159.3      .1       0
Bank Sta=143.5,159.3
XS Rating Curve= 0 ,0
Exp/Cntr(USF)=0,0
Exp/Cntr=0.3,0.1

Type RM Length L Ch R = 1 ,9611    ,185.5,181.9,183.7
XS GIS Cut Line= 4
2321192.74187395660191.0160431972321227.55689029660228.948822195
2321425.53481904660213.8796360182321474.89939445660171.270213034
#Sta/Elev= 30
       0 3113.29    22.8 3108.89    40.9 3103.02    56.1 3098.97    72.2 3087.34
    80.2 3080.15    96.2 3069.12     1023068.001   116.3 3067.26   121.33068.004
   132.3 3071.48   139.2 3072.16   160.4 3071.43   172.5 3073.72   176.5 3073.55
   184.5 3071.81   189.8 3071.65   196.5 3072.38   204.5 3074.84   212.6 3074.46
   216.6 3075.04   220.6 3076.56   236.6 3079.42   240.7 3080.91   251.1 3087.28
   264.1 3098.25   275.1 3105.02   289.3 3116.99   295.8 3123.82   315.2    3138
#Mann= 3 ,-1,0
       0      .1       0     102    .045       0   121.3      .1       0
Bank Sta=102,121.3
XS Rating Curve= 0 ,0
Exp/Cntr(USF)=0,0
Exp/Cntr=0.3,0.1

Type RM Length L Ch R = 1 ,9429    ,93,92,94
XS GIS Cut Line= 4
 2321217.1643481660285.5881771382321272.76444882660335.472379656
 2321429.1722088660359.3752266962321470.22275046660354.698582709
#Sta/Elev= 30
       0 3101.82    25.5 3097.09    57.8 3089.48    63.2 3087.65    73.9 3085.46
    78.1 3083.54    86.2 3077.09    94.3 3071.57   106.5 3065.03   110.5 3063.86
   122.7 3064.82   126.7 3063.39   146.9 3053.49     151 3054.03   159.1 3056.42
   167.2  3057.4   171.2 3057.34   175.3 3056.57   189.83051.493   191.4 3050.79
   195.5 3050.48   203.6 3051.51   207.6 3052.42   211.7 3055.44   227.9 3069.02
   235.9 3076.39   244.8 3083.29   256.1 3091.03   268.2 3102.08   274.2 3105.69
#Mann= 3 ,-1,0
       0      .1       0   189.8    .045       0   203.6      .1       0
#XS Ineff= 2 , 0
          168.95  3060.3
Permanent Ineff=
       F       F
Bank Sta=189.8,203.6
XS Rating Curve= 0 ,0
Exp/Cntr(USF)=0,0
Exp/Cntr=0.3,0.1

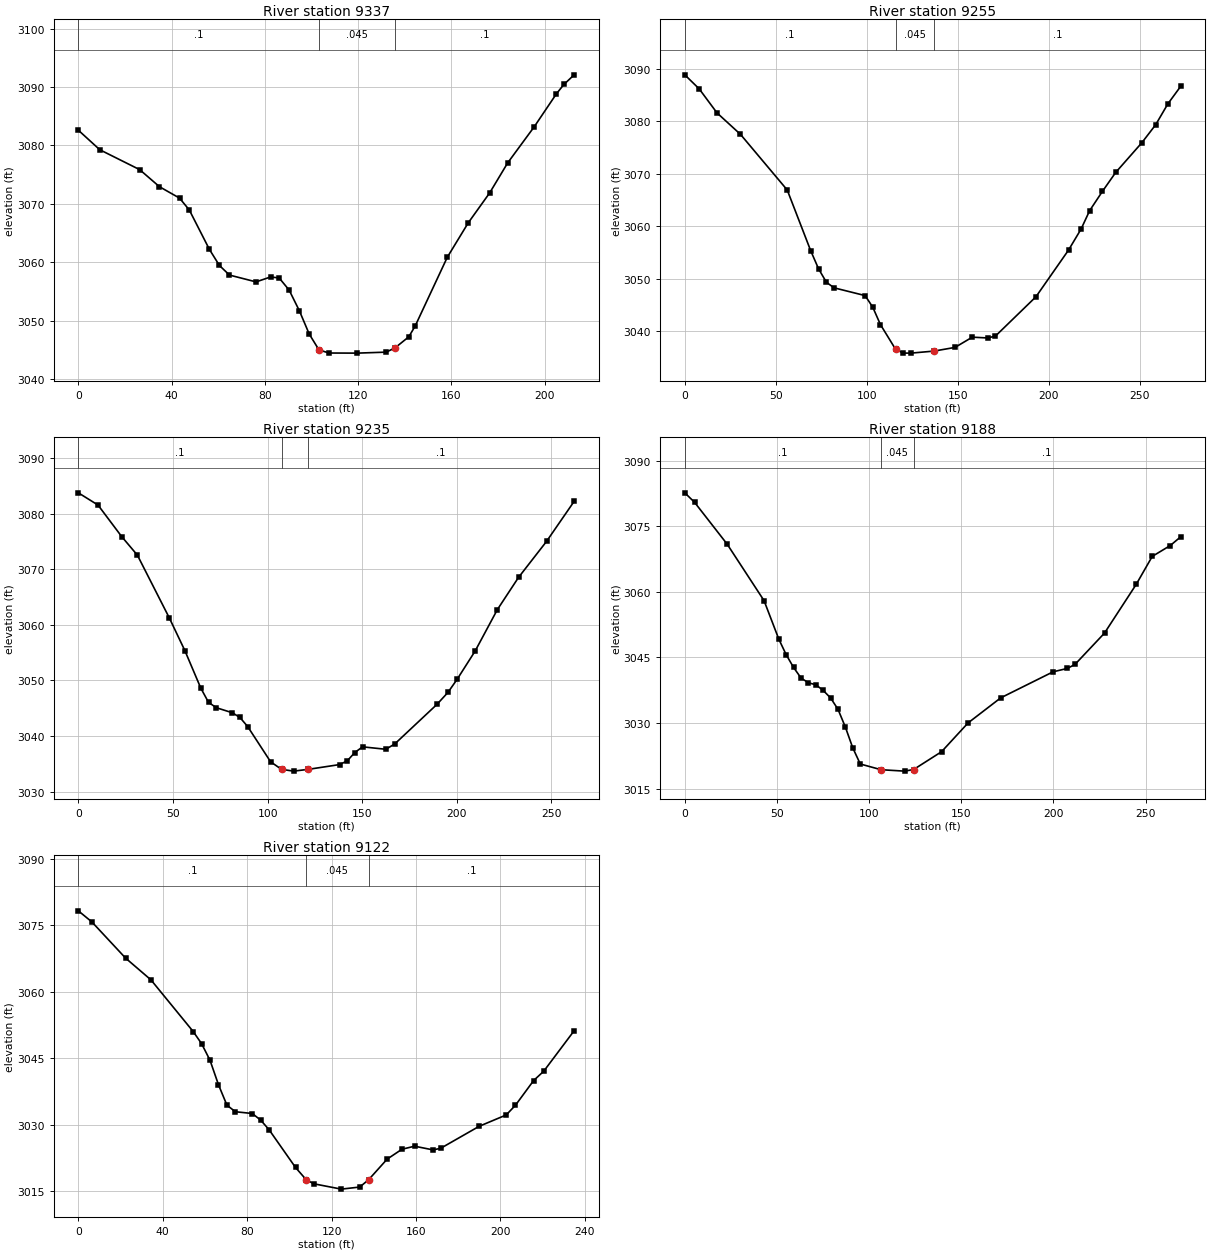
Type RM Length L Ch R = 1 ,9337    ,81.1,82.2,80.9
XS GIS Cut Line= 3
2321243.61418506660395.5559457012321391.54511492660451.552399375
2321443.36272876660434.837040069
#Sta/Elev= 30
       0 3082.62     9.2 3079.27    26.3 3075.86    34.8 3072.93    43.4 3070.98
    47.6 3068.93    56.2 3062.19    60.5 3059.43    64.8 3057.79    76.2 3056.62
    82.4 3057.46    86.1  3057.3    90.4 3055.21    94.8 3051.65      99 3047.68
   103.2 3044.95   107.5 3044.43   119.6 3044.41     132 3044.58   135.8 3045.31
   141.7 3047.21   144.4 3049.03   158.2 3060.84   167.2 3066.75   176.4 3071.89
   184.1 3077.02   195.5 3083.22     205 3088.86   208.2 3090.46   212.6 3092.11
#Mann= 3 ,-1,0
       0      .1       0   103.2    .045       0   135.8      .1       0
Bank Sta=103.2,135.8
XS Rating Curve= 0 ,0
Exp/Cntr(USF)=0,0
Exp/Cntr=0.3,0.1

Type RM Length L Ch R = 1 ,9255    ,19.6,19.6,18.8
XS GIS Cut Line= 4
2321203.65404325660467.4576654852321290.95139766660501.233427606
2321368.89546409660526.6951559752321449.95729319660473.693190799
#Sta/Elev= 30
       0 3088.84     7.9 3086.17    17.7 3081.59    30.6  3077.5    56.3  3066.9
    69.2 3055.33    73.5  3051.9    77.8 3049.34      82 3048.27    99.1 3046.79
   103.3 3044.58   107.5 3041.28   115.9 3036.53   120.1 3035.84   124.3 3035.83
     137 3036.22   148.5 3036.92     158 3038.87   166.4 3038.72   170.7 3039.07
     193 3046.57   210.9 3055.46   217.8 3059.47   222.5 3062.97   229.5 3066.63
   236.8 3070.24   251.2 3075.91   258.8 3079.34   265.5 3083.32   272.5 3086.63
#Mann= 3 ,-1,0
       0      .1       0   115.9    .045       0     137      .1       0
Bank Sta=115.9,137
XS Rating Curve= 0 ,0
Exp/Cntr(USF)=0,0
Exp/Cntr=0.3,0.1

Type RM Length L Ch R = 1 ,9235    ,47.7,46.7,43.9
XS GIS Cut Line= 4
 2321202.2372071660499.2398771312321281.41997606660522.934285902
2321359.32219605660534.9188160122321444.52843549660481.619181043
#Sta/Elev= 30
       0 3083.76    10.4 3081.56    22.9 3075.89    31.2 3072.55    48.1 3061.24
    56.3 3055.37    64.7 3048.63    68.8 3046.06      73 3045.09    81.4 3044.19
    85.4 3043.34    89.5  3041.7   101.6 3035.37   107.43034.004   113.8 3033.69
   121.5 3034.01   138.1 3034.87   142.1 3035.54   146.1 3037.04   150.2 3038.06
   162.5 3037.62   167.2 3038.58   189.5  3045.7   195.3 3047.85   200.2 3050.23
   209.7 3055.31   221.4 3062.74   232.6 3068.54   247.4 3075.02     262 3082.23
#Mann= 3 ,-1,0
       0      .1       0   107.4    .045       0   121.5      .1       0
Bank Sta=107.4,121.5
XS Rating Curve= 0 ,0
Exp/Cntr(USF)=0,0
Exp/Cntr=0.3,0.1

Type RM Length L Ch R = 1 ,9188    ,70.6,66.1,62.7
XS GIS Cut Line= 4
2321193.26150106660579.1774940412321256.24661876660575.209455639
2321368.89546409660565.6671891922321444.76102209660512.145596907
#Sta/Elev= 30
       0 3082.65     5.3 3080.48      23  3070.9      43 3057.99      51 3049.19
      55 3045.63      59 3042.72    63.1 3040.28    67.1  3039.2    71.1 3038.75
    75.1 3037.45    79.1 3035.74    83.1 3033.15    87.1 3029.09    91.1 3024.35
    95.2 3020.63   106.53019.322   119.2    3019   124.1 3019.36   139.3 3023.44
   153.7 3030.03   171.4 3035.76   199.8 3041.71   207.6  3042.5   211.7 3043.41
   227.7 3050.57   244.9 3061.71   253.6 3068.11   263.4  3070.6     269 3072.58
#Mann= 3 ,-1,0
       0      .1       0   106.5    .045       0   124.1      .1       0
Bank Sta=106.5,124.1
XS Rating Curve= 0 ,0
Exp/Cntr(USF)=0,0
Exp/Cntr=0.3,0.1

Type RM Length L Ch R = 1 ,9122    ,144,139.5,137
XS GIS Cut Line= 3
2321201.82578679660649.6294071492321298.77487077660645.450567322
2321425.81160149660591.961417544
#Sta/Elev= 30
       0 3078.31     6.4 3075.81    22.4 3067.62    34.4 3062.71    54.4 3051.04
    58.4 3048.29    62.4 3044.52    66.4    3039    70.4 3034.39    74.4 3032.91
    82.4 3032.51    86.4 3031.01    90.4 3028.82   102.9 3020.31     108 3017.52
   111.6 3016.62   124.6 3015.42   133.3 3015.89   137.53017.532   146.3  3022.2
   153.3 3024.43   159.3 3025.12     168 3024.29   171.6 3024.63   189.9 3029.62
   202.7 3032.18   207.1 3034.38   215.7 3039.96   220.5 3042.07   234.9 3051.22
#Mann= 3 ,-1,0
       0      .1       0     108    .045       0   137.5      .1       0
Bank Sta=108,137.5
XS Rating Curve= 0 ,0
Exp/Cntr(USF)=0,0
Exp/Cntr=0.3,0.1