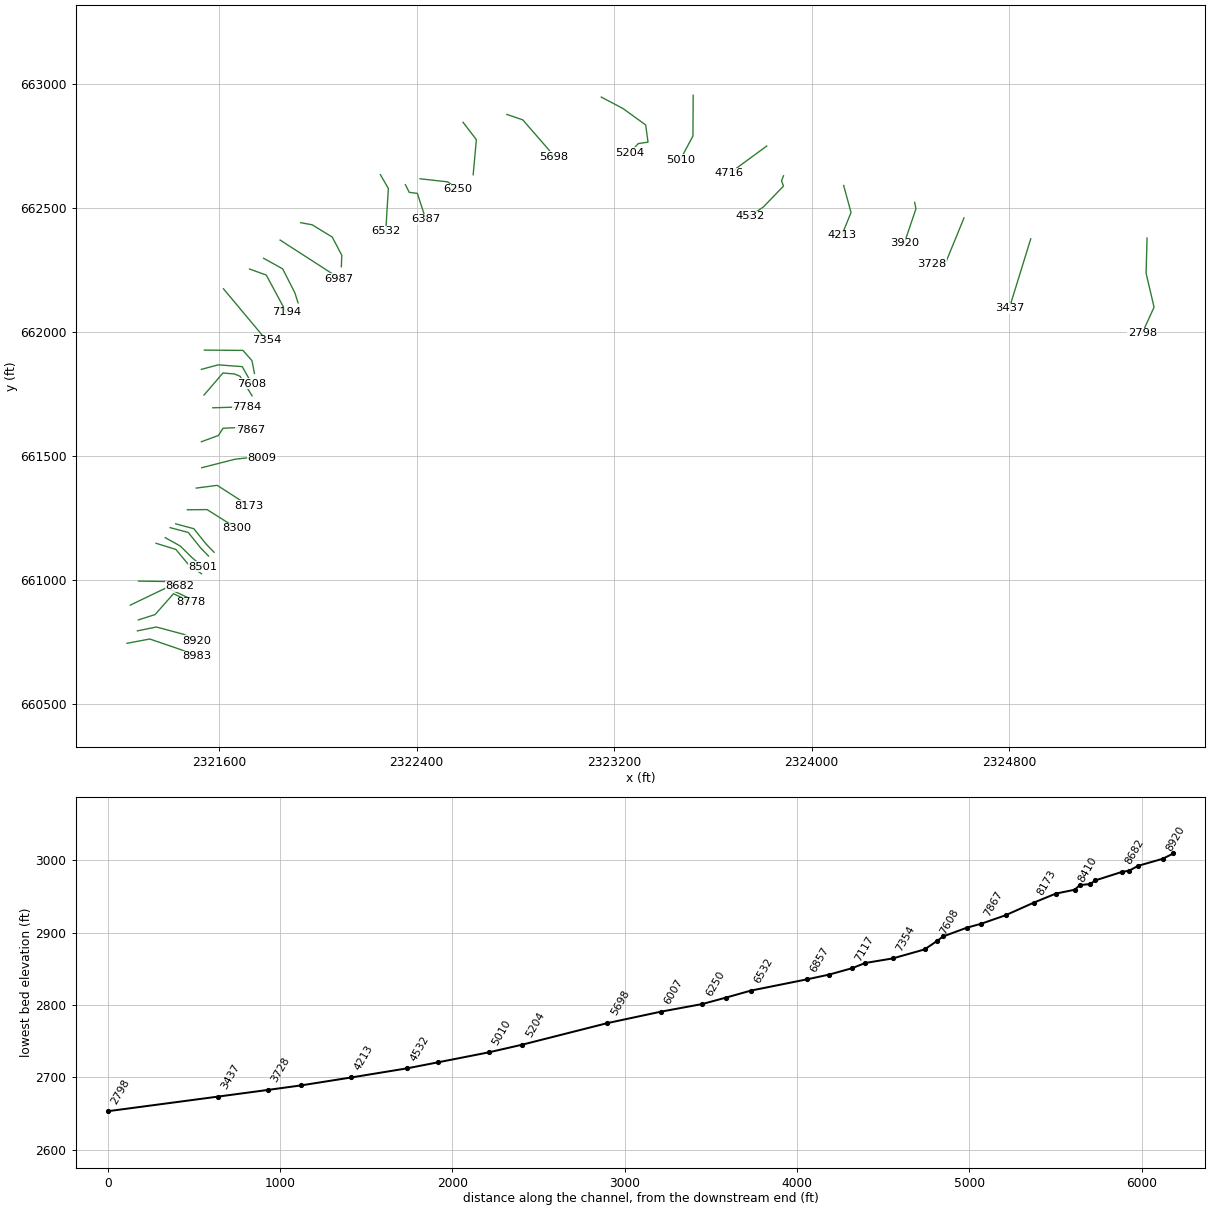
HEC-RAS study FISHHAWKCK.prj: FISHHAWKCK

--- FISHHAWKCK.g01 (geometry) --- (continued)

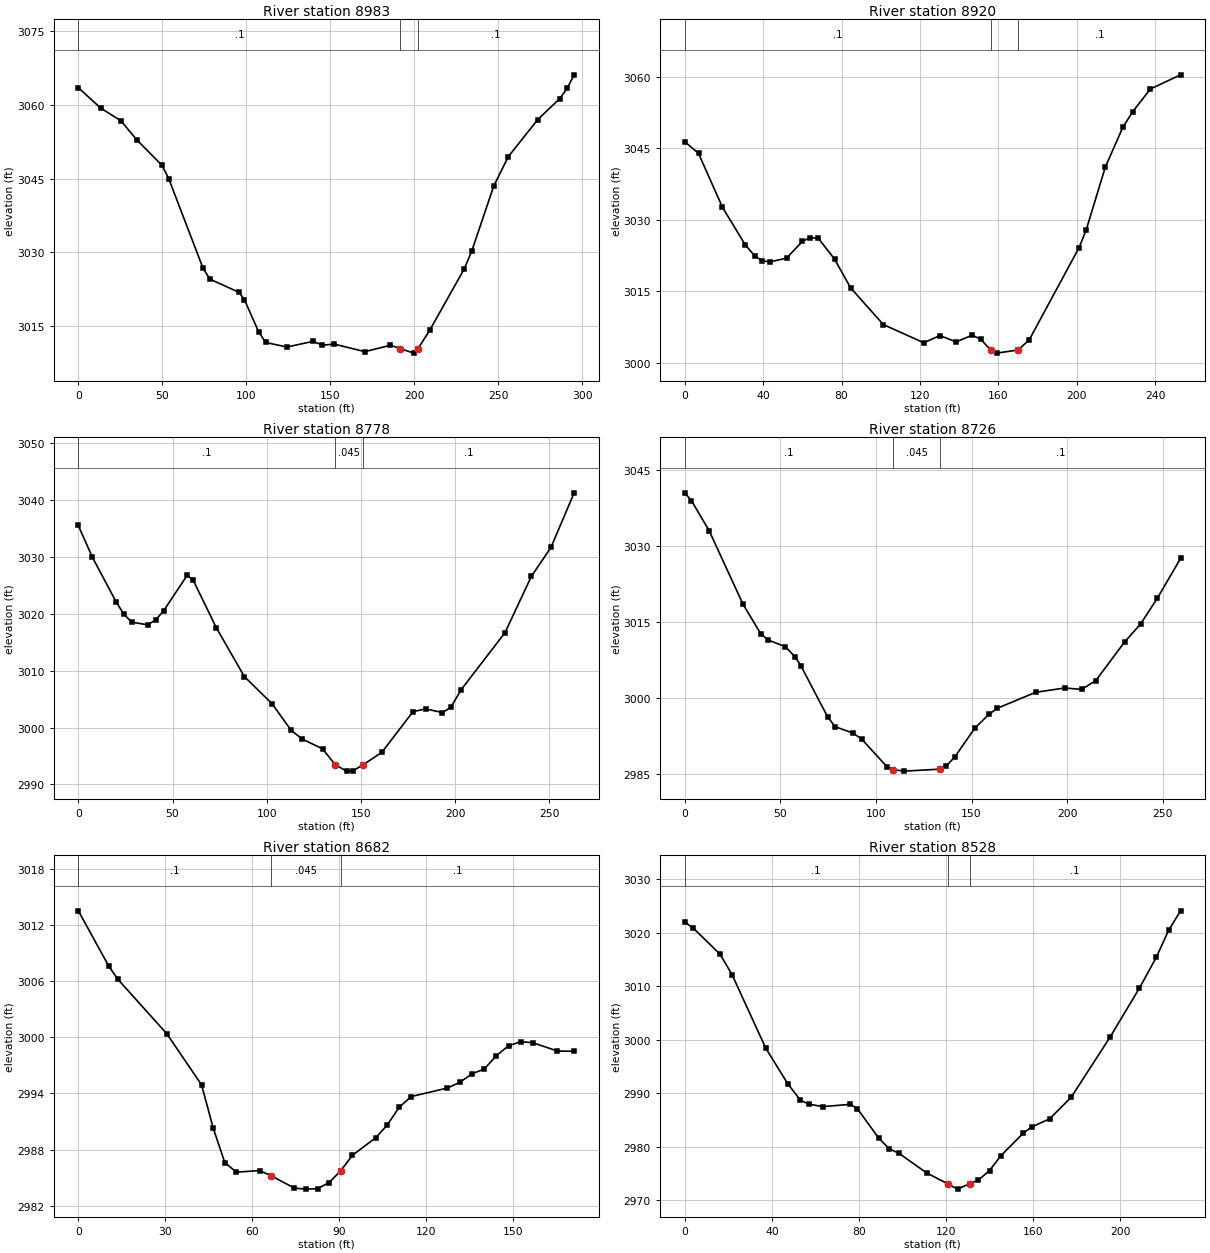
Type RM Length L Ch R = 1 ,8983    ,61.9,62.4,62.2
XS GIS Cut Line= 4
2321227.24511403660745.6296460472321319.42176699660762.886462356
2321449.05833829660718.6921766872321507.98405251660692.596503245
#Sta/Elev= 30
       0 3063.47    13.2 3059.36    25.4 3056.73    34.7  3052.9    49.8 3047.69
    53.8 3044.99    74.2  3026.8    78.3 3024.54    95.7 3021.85    98.9 3020.36
   107.3 3013.86   111.5 3011.66   124.2 3010.73   139.8 3011.89   145.3 3011.11
   152.4 3011.32   170.6 3009.79   185.8 3011.09   191.8  3010.4   199.7 3009.49
   202.33010.423   209.2 3014.14   229.8 3026.65   234.3  3030.3   247.3 3043.46
     256 3049.45   273.5 3056.98   286.6 3061.25     291 3063.32   295.2 3066.09
#Mann= 3 ,-1,0
       0      .1       0   191.8    .045       0   202.3      .1       0
Bank Sta=191.8,202.3
XS Rating Curve= 0 ,0
Exp/Cntr(USF)=0,0
Exp/Cntr=0.3,0.1

Type RM Length L Ch R = 1 ,8920    ,134.3,142.5,149.9
XS GIS Cut Line= 4
 2321269.3349099660795.7165031382321345.93833839660811.289727612
2321456.63450154660781.8268704992321510.50944026 660754.88940114
#Sta/Elev= 30
       0 3046.37       7 3043.93    19.2 3032.64    30.8 3024.78    35.6 3022.48
    39.6 3021.38    43.7 3021.21    51.9 3021.95      60 3025.49    64.1 3026.29
    68.2  3026.1    76.4 3021.77    84.6 3015.74   101.3 3008.04   121.9 3004.23
   130.2 3005.73   138.4  3004.4   146.7 3005.81   150.9 3004.98   156.13002.712
   159.1 3002.05     170  3002.7   175.7  3004.8   201.2 3024.19   204.8 3027.86
   214.6 3041.09   223.5 3049.38   228.6 3052.71   237.6 3057.44     253  3060.4
#Mann= 3 ,-1,0
       0      .1       0   156.1    .045       0     170      .1       0
Bank Sta=156.1,170
XS Rating Curve= 0 ,0
Exp/Cntr(USF)=0,0
Exp/Cntr=0.3,0.1

Type RM Length L Ch R = 1 ,8778    ,58.3,52.2,48.9
XS GIS Cut Line= 4
2321273.12299153660839.9107888062321340.88756289660861.376584703
2321415.38650159660945.5561764522321487.36005253660911.463441793
#Sta/Elev= 30
       0 3035.52     7.4 3029.97      20 3022.13    24.2  3019.9    28.4 3018.52
    36.8 3018.06      41 3018.91    45.2 3020.49    57.7 3026.74    60.8    3026
    73.3  3017.5    88.1 3008.96   102.9 3004.15   112.9 2999.51   118.9 2997.96
   129.6 2996.26   136.4 2993.44   142.4 2992.34   145.6 2992.37   150.9 2993.41
   161.1 2995.66   177.6  3002.8   184.4 3003.28   193.2 3002.63   197.6 3003.53
   203.1 3006.64   226.4 3016.68   240.4 3026.58   250.8 3031.67   263.1 3041.26
#Mann= 3 ,-1,0
       0      .1       0   136.4    .045       0   150.9      .1       0
Bank Sta=136.4,150.9
XS Rating Curve= 0 ,0
Exp/Cntr(USF)=0,0
Exp/Cntr=0.3,0.1

Type RM Length L Ch R = 1 ,8726    ,50.3,43.7,39.1
XS GIS Cut Line= 3
2321240.71384871660899.6782989482321387.60723631660969.968258059
2321475.15401173660929.141156061
#Sta/Elev= 30
       0 3040.48     3.5 3038.92    12.7 3033.04    30.4 3018.55    39.7 3012.71
    43.7 3011.44    52.6 3010.14    57.7 3008.12    60.7 3006.39    74.8 2996.24
    78.7 2994.36    88.1 2993.07    92.5 2991.92   105.7 2986.48   108.92985.897
   114.7 2985.59   133.52985.981   136.9 2986.65   141.3 2988.41   151.7 2994.05
     159 2996.76   163.5 2997.99   183.6 3001.14   198.8 3001.99   207.6 3001.71
     215 3003.44   230.1 3011.07   238.5 3014.63   247.3 3019.74   259.4 3027.56
#Mann= 3 ,-1,0
       0      .1       0   108.9    .045       0   133.5      .1       0
Bank Sta=108.9,133.5
XS Rating Curve= 0 ,0
Exp/Cntr(USF)=0,0
Exp/Cntr=0.3,0.1

Type RM Length L Ch R = 1 ,8682    ,161.1,154.3,140.1
XS GIS Cut Line= 3
2321273.70183181660996.473112744 2321382.3516673660994.801576814
2321441.69119283660975.578913612
#Sta/Elev= 30
       0 3013.49    10.5 3007.59    13.6 3006.19    30.5 3000.38    42.5 2994.92
    46.5 2990.32    50.5 2986.63    54.5  2985.6    62.5 2985.77    66.5 2985.22
    74.5  2983.9    78.5 2983.79    82.5 2983.84    86.5 2984.49    90.5 2985.75
    94.5 2987.39   102.5 2989.26   106.5 2990.61   110.6 2992.51   114.8 2993.67
   127.3 2994.58   131.6 2995.19   135.8 2996.11     140  2996.6   144.2 2998.05
   148.4 2999.09   152.6 2999.53   156.8 2999.41   165.2 2998.53     171  2998.5
#Mann= 3 ,-1,0
       0      .1       0    66.5    .045       0    90.5      .1       0
Bank Sta=66.5,90.5
XS Rating Curve= 0 ,0
Exp/Cntr(USF)=0,0
Exp/Cntr=0.3,0.1

Type RM Length L Ch R = 1 ,8528    ,26.1,26.4,27
XS GIS Cut Line= 4
2321344.67564452661148.8498905272321425.06715464 661124.01691096
2321472.20772602661067.6165844882321528.60805249661025.947686572
#Sta/Elev= 30
       0 3021.93     3.7 3020.89    16.2 3015.95    21.7 3012.13    37.2 2998.39
    47.3 2991.75    53.1 2988.68    56.9 2987.95    63.3 2987.47    76.1  2987.9
    79.3 2987.08      89 2981.64      94 2979.57    98.3 2978.78   111.1 2975.09
   120.72973.076   125.3 2972.06   130.92973.083   134.8 2973.73     140 2975.52
   145.1 2978.25   155.6 2982.55   159.4 2983.68   167.6 2985.19   177.5 2989.21
   195.4 3000.47   208.9 3009.63   216.6 3015.34   222.3 3020.42   227.8 3024.05
#Mann= 3 ,-1,0
       0      .1       0   120.7    .045       0   130.9      .1       0
Bank Sta=120.7,130.9
XS Rating Curve= 0 ,0
Exp/Cntr(USF)=0,0
Exp/Cntr=0.3,0.1

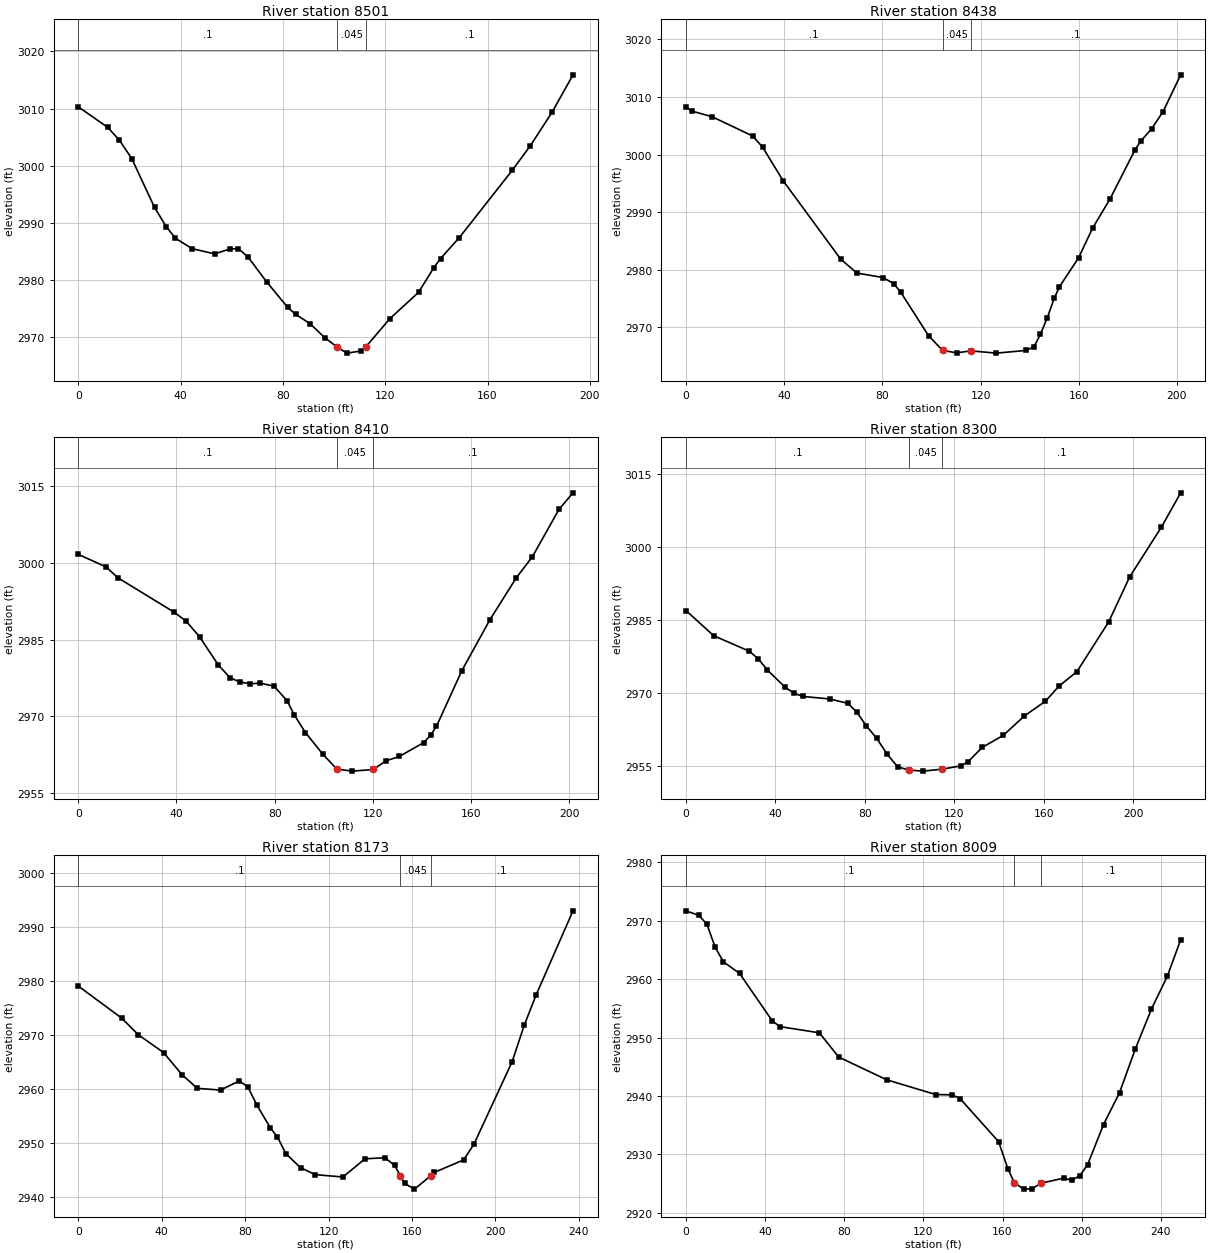
Type RM Length L Ch R = 1 ,8501    ,62.8,63,61.3
XS GIS Cut Line= 4
2321382.13556285661171.5783802992321442.74486891661137.906543599
2321491.14813416661090.3450742612321534.50062391661054.568747767
#Sta/Elev= 30
       0 3010.32    11.5 3006.73    16.1 3004.48    20.9 3001.27    29.8 2992.74
    34.4 2989.36    37.9 2987.37    44.4 2985.54    53.3 2984.61    59.2 2985.46
    62.6 2985.54    66.4 2984.03    73.7 2979.69    81.8 2975.29      85 2974.04
    90.7 2972.38    96.3 2969.98   101.22968.327     105 2967.26   110.5 2967.63
   112.42968.357   121.8 2973.28     133 2977.88     139  2982.2   141.6 2983.79
   148.9 2987.42   169.6 2999.19   176.7  3003.5   185.2 3009.36   193.4 3015.91
#Mann= 3 ,-1,0
       0      .1       0   101.2    .045       0   112.4      .1       0
Bank Sta=101.2,112.4
XS Rating Curve= 0 ,0
Exp/Cntr(USF)=0,0
Exp/Cntr=0.3,0.1

Type RM Length L Ch R = 1 ,8438    ,27.3,27.8,27.8
XS GIS Cut Line= 4
2321401.91776691661211.9845843392321475.15401173661192.623278236
2321525.66176678661129.9094823832321557.22911369661097.500339559
#Sta/Elev= 30
       0 3008.28     2.3 3007.56    10.6 3006.58    27.2 3003.22    31.3 3001.24
    39.6 2995.45      63 2981.87    69.6 2979.45    80.2 2978.67    84.6 2977.63
    87.5  2976.1    98.8 2968.58   104.5 2966.03   110.2  2965.6   116.1 2965.94
   126.4 2965.55   138.7 2966.02   141.8 2966.68   144.4 2968.84   147.2 2971.71
     150 2975.07   152.1 2977.05   159.9 2982.08   165.6 2987.22   172.7 2992.28
   182.8 3000.74   185.2 3002.31   189.7 3004.51   194.3 3007.44   201.5 3013.84
#Mann= 3 ,-1,0
       0      .1       0   104.5    .045       0   116.1      .1       0
Bank Sta=104.5,116.1
XS Rating Curve= 0 ,0
Exp/Cntr(USF)=0,0
Exp/Cntr=0.3,0.1

Type RM Length L Ch R = 1 ,8410    ,107,110.3,111.9
XS GIS Cut Line= 4
 2321424.4358077661227.1369108532321497.67205252661207.775604751
2321548.17980757661145.0618088982321579.74715448661112.652666074
#Sta/Elev= 30
       0 3001.67    11.2 2999.24    16.3 2997.04      39 2990.38    43.9 2988.64
    49.4 2985.56      57 2980.08    61.8 2977.57    65.9 2976.72    70.1  2976.4
    74.2  2976.5    79.7 2975.93    85.1 2973.05    87.9 2970.35    92.5 2966.86
    99.6 2962.63   105.3 2959.72   111.6 2959.32   120.2 2959.64   125.3 2961.33
   130.8 2962.19   140.7  2964.9   143.5 2966.33   145.9 2968.08   156.2 2978.93
   167.7 2988.94   178.4 2997.09   184.9 3001.16   195.8 3010.46   201.5 3013.69
#Mann= 3 ,-1,0
       0      .1       0   105.3    .045       0   120.2      .1       0
Bank Sta=105.3,120.2
XS Rating Curve= 0 ,0
Exp/Cntr(USF)=0,0
Exp/Cntr=0.3,0.1

Type RM Length L Ch R = 1 ,8300    ,126.4,127.1,125.5
XS GIS Cut Line= 3
2321471.77883958661283.9772928042321551.17679629661284.813060769
2321671.52738329661209.593943893
#Sta/Elev= 30
       0 2986.96    12.4 2981.78    28.4 2978.58    32.4 2976.99    36.4 2974.74
    44.4 2971.17    48.4 2969.92    52.4 2969.29    64.4 2968.77    72.4 2967.87
    76.4 2966.09    80.6 2963.28    85.3 2960.71      90 2957.42    94.7 2954.83
    99.72954.156     106 2953.94   114.7 2954.35     123 2955.02   126.3 2955.91
   132.5 2958.81   141.9 2961.27   151.3 2965.25   160.8 2968.31   166.9 2971.43
   174.9  2974.4   189.1 2984.62   198.5 2993.88   212.7 3004.11   221.3 3011.15
#Mann= 3 ,-1,0
       0      .1       0    99.7    .045       0   114.7      .1       0
Bank Sta=99.7,114.7
XS Rating Curve= 0 ,0
Exp/Cntr(USF)=0,0
Exp/Cntr=0.3,0.1

Type RM Length L Ch R = 1 ,8173    ,158.7,164.2,168.1
XS GIS Cut Line= 3
2321507.56315455661371.5049107042321592.58454222661382.448257631
2321720.11662372661300.794053634
#Sta/Elev= 30
       0 2979.14    20.8  2973.2    28.8 2970.11    40.9 2966.82    49.7 2962.73
    57.1 2960.19    68.2 2959.87    77.2 2961.57    81.3 2960.44    85.7 2957.04
    92.1 2952.87    95.5 2951.16    99.5  2948.1   106.6 2945.48   113.7  2944.2
   126.9 2943.77   137.5 2947.14     147 2947.33   151.7 2945.91   154.42944.013
   156.5 2942.57   161.2 2941.52     1692943.993   170.7 2944.62   184.8 2946.94
   189.7 2949.84     208 2965.11   213.8 2971.86   219.5 2977.48   237.2 2993.07
#Mann= 3 ,-1,0
       0      .1       0   154.4    .045       0     169      .1       0
Bank Sta=154.4,169
XS Rating Curve= 0 ,0
Exp/Cntr(USF)=0,0
Exp/Cntr=0.3,0.1

Type RM Length L Ch R = 1 ,8009    ,141.2,141.9,139.2
XS GIS Cut Line= 4
2321529.87074637661453.5800126592321663.71629725661487.672747318
2321744.94960329 661496.932502412321774.83335836 661493.56531874
#Sta/Elev= 30
       0 2971.69     6.5 2970.92    10.6 2969.39    14.7 2965.52    18.9 2962.97
    27.1 2960.97    43.7 2952.81    47.6 2951.86    67.4 2950.81    77.2 2946.66
   101.4 2942.77   126.2 2940.24   134.5 2940.19   138.6 2939.52     158 2932.17
   162.7 2927.52     166  2925.1   170.8 2924.05   174.8 2924.11   179.52925.066
   190.9 2925.93   194.9 2925.57     199 2926.33     203 2928.26     211  2935.1
   219.1 2940.56   227.1 2948.06   235.2 2954.85   243.3 2960.53     250 2966.75
#Mann= 3 ,-1,0
       0      .1       0     166    .045       0   179.5      .1       0
Bank Sta=166,179.5
XS Rating Curve= 0 ,0
Exp/Cntr(USF)=0,0
Exp/Cntr=0.3,0.1

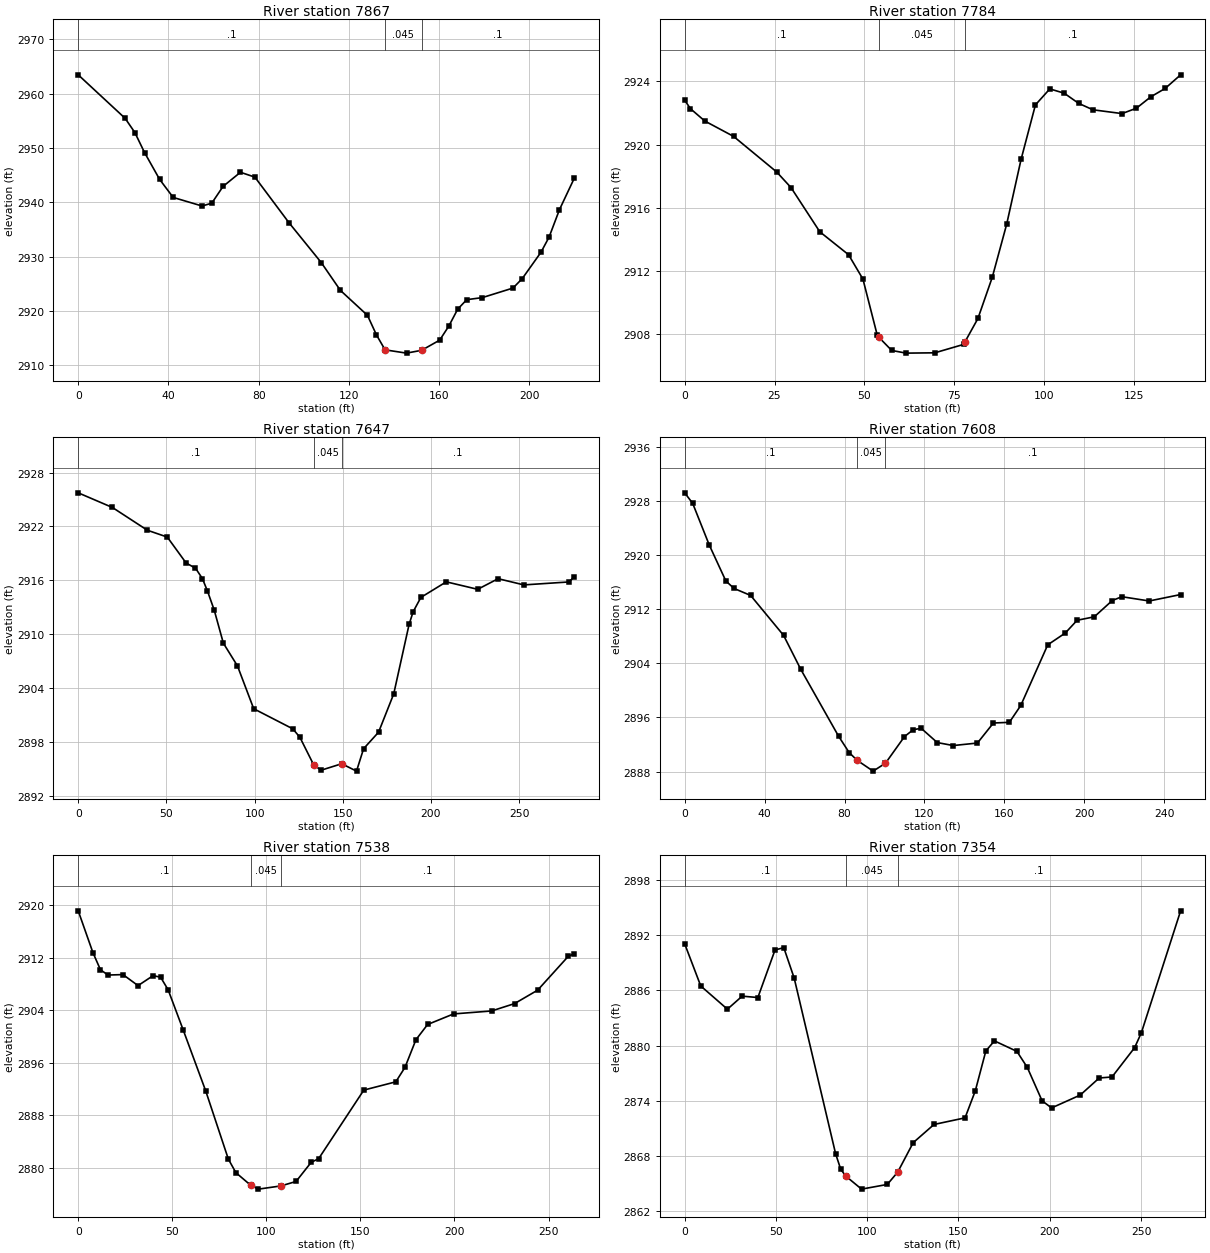
Type RM Length L Ch R = 1 ,7867    ,84.3,83.3,83.1
XS GIS Cut Line= 5
2321528.60805249661558.3836043872321597.63531773661583.637481912
2321615.73392995661612.6794410652321686.86568498661616.046624735
 2321726.4300931661605.945073726
#Sta/Elev= 30
       0 2963.48    20.8 2955.47    25.1 2952.86    29.4 2949.17    36.1 2944.22
    42.1 2940.91    54.9 2939.33    59.2 2939.86    64.2 2942.94    71.9 2945.54
    78.3 2944.65    93.4 2936.26   107.7 2928.93   116.2  2923.8   128.2  2919.2
   132.2 2915.59     1362912.855   145.5 2912.25   152.2 2912.77   160.2 2914.64
   164.2 2917.19   168.2 2920.35   172.2 2922.09   179.1 2922.47   192.7 2924.23
   196.8 2925.97   205.1 2930.82   208.7 2933.62   213.3 2938.67   219.8  2944.4
#Mann= 3 ,-1,0
       0      .1       0     136    .045       0   152.2      .1       0
Bank Sta=136,152.2
XS Rating Curve= 0 ,0
Exp/Cntr(USF)=0,0
Exp/Cntr=0.3,0.1

Type RM Length L Ch R = 1 ,7784    ,137.5,136.8,135.3
XS GIS Cut Line= 2
2321574.57829931661695.1751317272321712.48001359661699.353971553
#Sta/Elev= 30
       0 2922.81     1.6 2922.27     5.6 2921.49    13.6 2920.52    25.6 2918.27
    29.6 2917.28    37.6 2914.49    45.6 2913.04    49.6  2911.5    53.6 2907.94
      54 2907.83    57.6 2906.99    61.6 2906.82    69.6 2906.84    77.6 2907.37
      782907.534    81.6 2909.01    85.6 2911.62    89.6 2914.97    93.6 2919.06
    97.6 2922.51   101.6 2923.52   105.6 2923.25   109.6 2922.61   113.6  2922.2
   121.7 2921.96   125.7  2922.3   129.7 2923.02   133.7 2923.55     138 2924.41
#Mann= 3 ,-1,0
       0      .1       0      54    .045       0      78      .1       0
Bank Sta=54,78
XS Rating Curve= 0 ,0
Exp/Cntr(USF)=0,0
Exp/Cntr=0.3,0.1

Type RM Length L Ch R = 1 ,7647    ,40.2,38.5,41.6
XS GIS Cut Line= 5
2321539.20986095661746.8253874662321615.81328944661835.634856762
2321662.95386082661831.4258771762321685.26145264661822.166122083
2321733.66471789661743.458203797
#Sta/Elev= 30
       0 2925.74    19.4 2924.11    39.2 2921.58    50.5 2920.82    61.2 2917.93
    66.5 2917.36    70.4 2916.21    73.3 2914.81    77.1 2912.71    82.3 2909.02
    90.3 2906.49    99.5 2901.73   121.7 2899.49   125.7 2898.55   133.52895.492
   137.7 2894.89   149.4 2895.61   157.8 2894.79   161.8 2897.28   170.3 2899.12
   178.9 2903.38   187.6  2911.1   189.9 2912.51   194.3 2914.11   208.7 2915.84
   226.5 2915.01   238.1 2916.19   252.7  2915.5   278.3 2915.83   281.2  2916.4
#Mann= 3 ,-1,0
       0      .1       0   133.5    .045       0   149.4      .1       0
Bank Sta=133.5,149.4
XS Rating Curve= 0 ,0
Exp/Cntr(USF)=0,0
Exp/Cntr=0.3,0.1

Type RM Length L Ch R = 1 ,7608    ,66.6,69.9,68.8
XS GIS Cut Line= 4
2321528.30457059661850.1922957272321596.47007106661868.385115108
2321693.88225585661861.2461606682321733.03136084661791.468638232
#Sta/Elev= 30
       0 2929.18       4 2927.63    12.3 2921.47    20.6 2916.16    24.7 2915.05
      33 2914.02    49.5 2908.12    58.1  2903.1      77 2893.23    82.3 2890.81
    86.3 2889.66    94.3 2888.06   100.52889.231     110 2893.16   114.4 2894.19
   118.4 2894.38   126.4 2892.28   134.4 2891.84   146.5 2892.21   154.5 2895.17
   162.5 2895.27   168.2 2897.76   181.7 2906.72   190.5 2908.47   196.4 2910.35
     205 2910.86     214 2913.27   218.8 2913.83   232.5  2913.2   248.2 2914.15
#Mann= 3 ,-1,0
       0      .1       0    86.3    .045       0   100.5      .1       0
Bank Sta=86.3,100.5
XS Rating Curve= 0 ,0
Exp/Cntr(USF)=0,0
Exp/Cntr=0.3,0.1

Type RM Length L Ch R = 1 ,7538    ,196.3,184.5,176.3
XS GIS Cut Line= 4
2321540.39319534661927.9320121672321696.54633803 661926.66931829
2321733.16446044661885.4213183332321743.26601145661834.071767366
#Sta/Elev= 30
       0 2919.16     7.8 2912.81    11.8  2910.2    15.8 2909.38    23.8 2909.45
    31.8 2907.77    39.8 2909.29    43.8 2909.05    47.8 2907.13    55.8 2901.02
    67.8 2891.71    79.8 2881.35    83.8 2879.29    91.8 2877.34    95.8 2876.78
   107.8 2877.27   115.8 2877.95   123.8 2880.85   127.8 2881.42   151.8 2891.86
   168.8 2893.12   173.7 2895.33   179.5 2899.53   185.7 2901.85   199.5 2903.46
   219.7 2903.91   231.9 2905.03   244.2 2907.08   260.5 2912.24   263.6 2912.62
#Mann= 3 ,-1,0
       0      .1       0    91.8    .045       0   107.8      .1       0
Bank Sta=91.8,107.8
XS Rating Curve= 0 ,0
Exp/Cntr(USF)=0,0
Exp/Cntr=0.3,0.1

Type RM Length L Ch R = 1 ,7354    ,162.4,159.8,157.7
XS GIS Cut Line= 2
2321617.67766441662175.1295736112321792.35316915661967.023350253
#Sta/Elev= 30
       0 2891.08     8.8 2886.49    23.4 2883.96    31.5 2885.38    40.1 2885.23
    49.5 2890.41    54.3 2890.66      60 2887.34    82.7 2868.21    85.5 2866.53
    88.3 2865.78    96.9 2864.37     111 2864.88   116.7 2866.22   125.2 2869.43
   136.6 2871.41   153.6 2872.13   159.2 2875.06     165 2879.42   169.7 2880.51
     182 2879.37   187.7 2877.62   195.8 2873.99     201 2873.21   216.7 2874.61
   227.1 2876.47   234.1 2876.58   246.5 2879.77   250.2  2881.4   271.7 2894.67
#Mann= 3 ,-1,0
       0      .1       0    88.3    .045       0   116.7      .1       0
Bank Sta=88.3,116.7
XS Rating Curve= 0 ,0
Exp/Cntr(USF)=0,0
Exp/Cntr=0.3,0.1

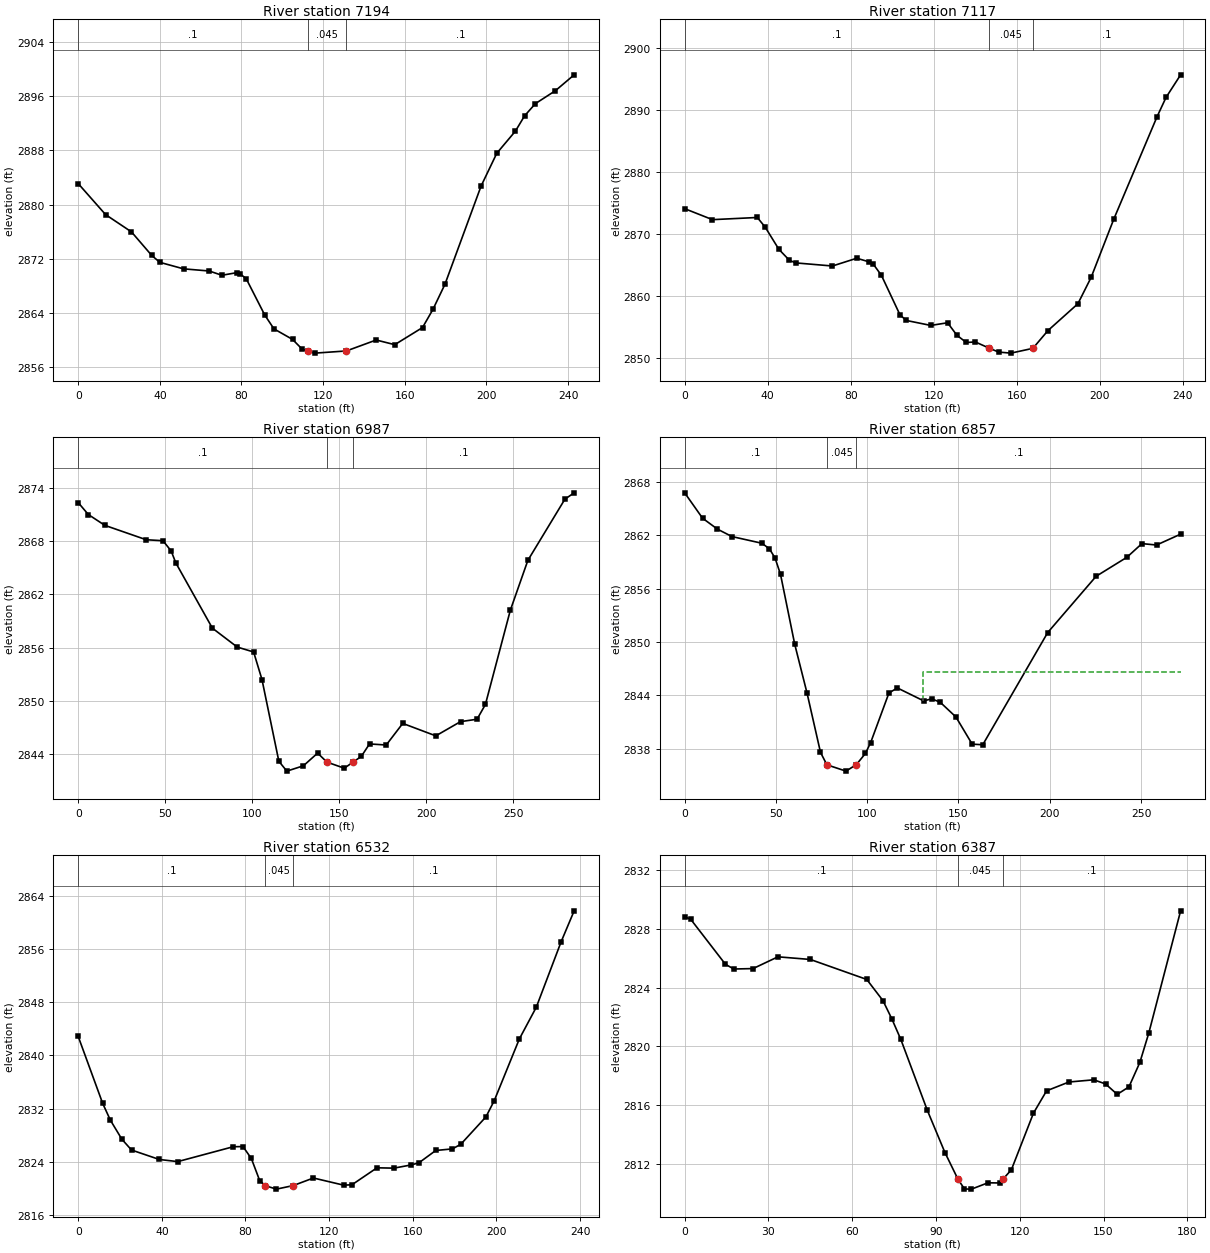
Type RM Length L Ch R = 1 ,7194    ,75.3,77,75.6
XS GIS Cut Line= 3
2321723.60893392662254.7001294722321791.16045816662230.450864359
2321872.56870533662079.759002586
#Sta/Elev= 30
       0 2883.09    13.4 2878.51    26.1 2875.95      36 2872.48      40 2871.45
    51.6 2870.49    64.2 2870.17    70.4 2869.54    77.8 2869.93    79.4 2869.73
    82.3 2869.04    91.4 2863.66    95.9 2861.62     105 2860.06   109.6 2858.66
   112.42858.287     116 2858.03   131.42858.352     146 2859.97   155.1 2859.28
   168.7 2861.81   173.8 2864.49   179.7 2868.21   197.4 2882.73   205.1 2887.58
   214.2 2890.84   218.7  2893.1     224 2894.91   233.8 2896.82     243 2899.17
#Mann= 3 ,-1,0
       0      .1       0   112.4    .045       0   131.4      .1       0
Bank Sta=112.4,131.4
XS Rating Curve= 0 ,0
Exp/Cntr(USF)=0,0
Exp/Cntr=0.3,0.1

Type RM Length L Ch R = 1 ,7117    ,124.8,130.3,135.3
XS GIS Cut Line= 4
 2321780.4070182662298.0869082622321857.57164397662255.529447988
2321907.14407022662158.2552530782321919.77100899662118.503779196
#Sta/Elev= 30
       0 2874.13    13.4 2872.36      35 2872.71    38.8 2871.15    45.4 2867.57
    50.5 2865.79    53.5 2865.38    71.2 2864.88    82.9 2866.13    88.8 2865.56
    90.8 2865.22    94.8 2863.38   103.7 2857.04   106.7  2856.1   118.6 2855.29
   126.7 2855.72   131.2  2853.7   135.7 2852.54   140.1 2852.62   146.7 2851.63
   151.3 2850.99   157.2 2850.82   167.82851.591   175.1 2854.47   189.5 2858.79
   195.9 2863.06   206.8 2872.45   227.6 2888.94     232  2892.1     239 2895.73
#Mann= 3 ,-1,0
       0      .1       0   146.7    .045       0   167.8      .1       0
Bank Sta=146.7,167.8
XS Rating Curve= 0 ,0
Exp/Cntr(USF)=0,0
Exp/Cntr=0.3,0.1

Type RM Length L Ch R = 1 ,6987    ,129.7,129.4,129.6
XS GIS Cut Line= 3
 2321847.2830272662371.5102188432322057.73200657662236.355207645
2322084.85654169662214.374980911
#Sta/Elev= 30
       0 2872.34     5.8    2871    15.3 2869.78    39.1 2868.16    48.7 2868.05
    53.4  2866.9    56.1 2865.55    77.1 2858.21    91.4 2856.08   100.8 2855.53
   105.6 2852.43   115.3 2843.23   119.9 2842.12   129.4 2842.72   137.6 2844.15
   142.92843.137   152.9 2842.45   157.9 2843.13   162.7 2843.78   167.4 2845.18
     177 2845.06   186.5 2847.49   205.5 2846.09   219.7 2847.69   229.2 2847.96
     234 2849.62   248.3 2860.21   258.4 2865.84   279.7 2872.73     285 2873.44
#Mann= 3 ,-1,0
       0      .1       0   142.9    .045       0   157.9      .1       0
Bank Sta=142.9,157.9
XS Rating Curve= 0 ,0
Exp/Cntr(USF)=0,0
Exp/Cntr=0.3,0.1

Type RM Length L Ch R = 1 ,6857    ,333.2,325.9,317.1
XS GIS Cut Line= 5
2321930.52729015662441.6598786342321976.82606562662433.241919459
2322058.19967097662383.6694932072322097.01581606662310.246182625
2322095.14515846662263.947407163
#Sta/Elev= 30
       0 2866.75     9.8  2863.9    17.9 2862.68    25.9 2861.84    42.3 2861.09
    46.4 2860.47    49.5 2859.44    52.5  2857.6    60.3 2849.74      67  2844.3
    74.4 2837.62    77.9 2836.22    88.4 2835.51    94.1 2836.25      99 2837.49
   101.9 2838.72   111.9 2844.28   116.5 2844.85     131 2843.39   135.3 2843.63
     140 2843.24   148.6 2841.59   157.5 2838.54   163.3 2838.47   198.9 2851.07
   225.4 2857.38   242.3 2859.52   250.5 2861.05   258.5 2860.89   271.7 2862.11
#Mann= 3 ,-1,0
       0      .1       0    77.9    .045       0    94.1      .1       0
#XS Ineff= 2 , 0
                          130.61          2846.6
Permanent Ineff=
       F       F
Bank Sta=77.9,94.1
XS Rating Curve= 0 ,0
Exp/Cntr(USF)=0,0
Exp/Cntr=0.3,0.1

Type RM Length L Ch R = 1 ,6532    ,142.4,144.6,148.4
XS GIS Cut Line= 4
2322253.21572519662635.272939658 2322285.4845687662579.620876224
2322276.13128072662425.2916246832322276.13128072662407.052713137
#Sta/Elev= 30
       0 2842.85    11.7 2832.81    15.4 2830.28    20.9 2827.42    25.5 2825.81
    38.8 2824.39    47.6 2824.07    74.1  2826.3    78.8 2826.33    82.8 2824.54
    86.8 2821.22    89.5 2820.45    94.8 2819.94   102.8 2820.47   112.5 2821.61
   126.9 2820.54   130.9 2820.59   142.9 2823.14     151 2823.09   159.4 2823.58
     163  2823.9     171 2825.74     179 2825.98     183 2826.68     195 2830.78
     199 2833.23     211 2842.49   219.1 2847.25     231 2857.09   237.2 2861.71
#Mann= 3 ,-1,0
       0      .1       0    89.5    .045       0   102.8      .1       0
Bank Sta=89.5,102.8
XS Rating Curve= 0 ,0
Exp/Cntr(USF)=0,0
Exp/Cntr=0.3,0.1

Type RM Length L Ch R = 1 ,6387    ,130.7,137.4,150.4
XS GIS Cut Line= 4
2322354.45103756662595.0483297042322369.98217224662563.986060349
2322402.93848241662559.8191705572322437.03121706662455.646925767
#Sta/Elev= 30
       0  2828.8     2.1 2828.66    14.6 2825.58    17.6 2825.26    24.5 2825.29
    33.4 2826.09      45 2825.91    65.2 2824.55      71 2823.11    74.2 2821.86
    77.4 2820.47    86.9 2815.64    93.2 2812.77    97.92810.941   100.2 2810.29
   102.7 2810.28   108.6 2810.71   112.8  2810.7   113.9 2810.94     117  2811.6
   124.9 2815.45   129.6 2816.97   137.6 2817.57   146.5 2817.72   150.7 2817.44
   154.9 2816.73   159.1 2817.24     163  2818.9   166.2  2820.9   177.6 2829.22
#Mann= 3 ,-1,0
       0      .1       0    97.9    .045       0   113.9      .1       0
Bank Sta=97.9,113.9
XS Rating Curve= 0 ,0
Exp/Cntr(USF)=0,0
Exp/Cntr=0.3,0.1

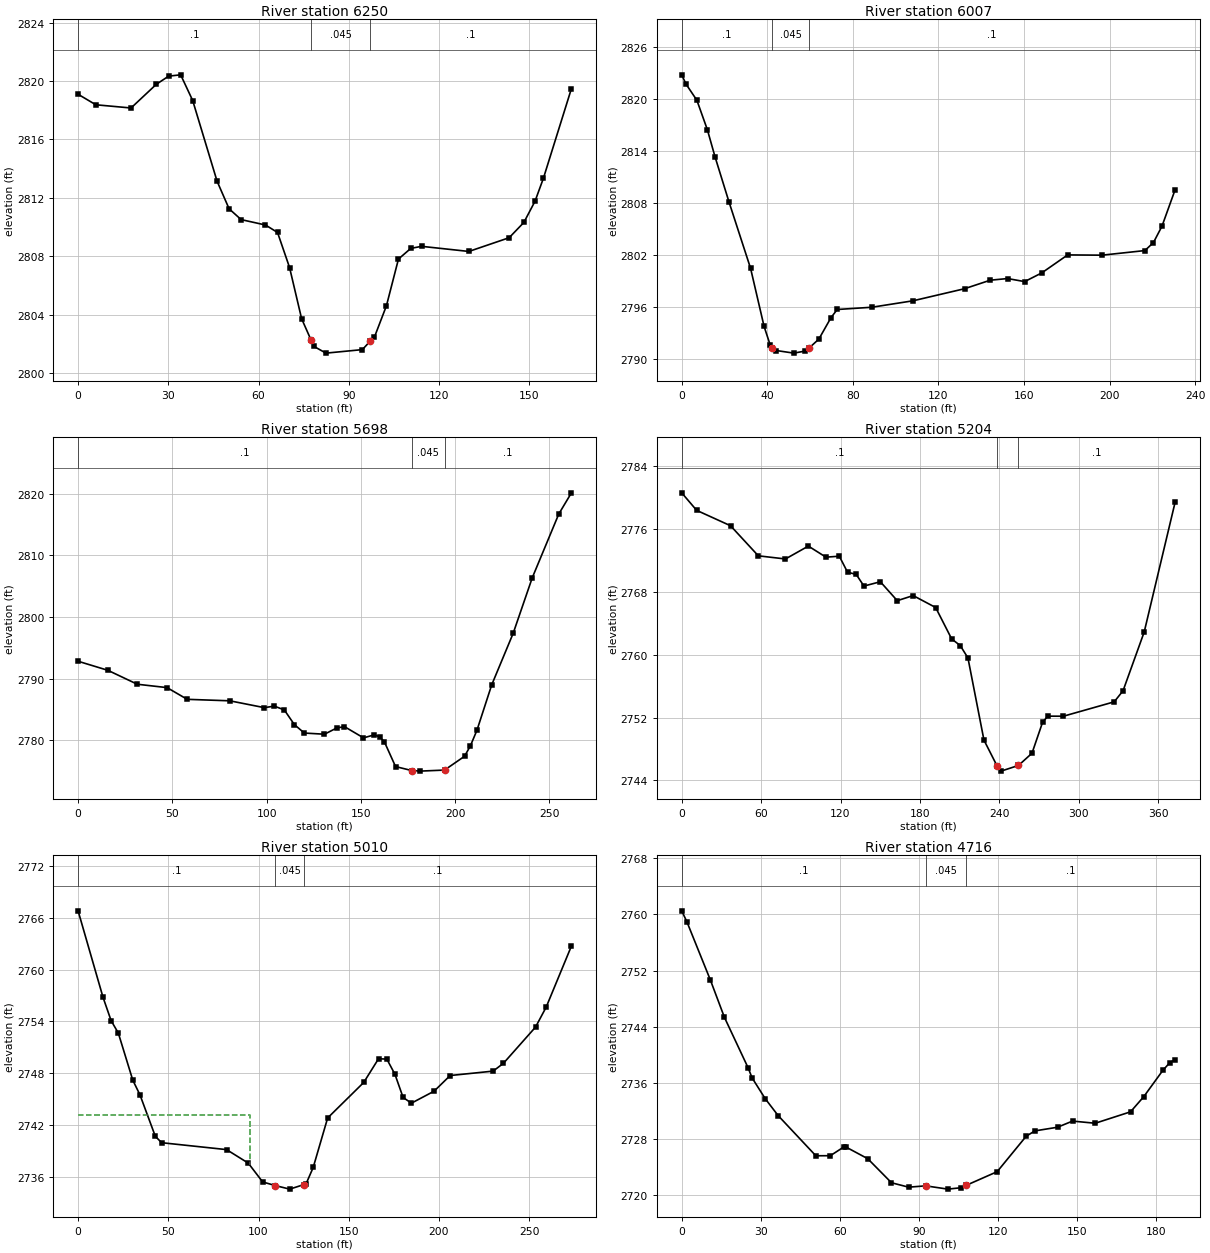
Type RM Length L Ch R = 1 ,6250    ,248.7,242.1,234.1
XS GIS Cut Line= 3
2322414.28999934662618.6887243672322526.03840739662606.188054992
 2322567.7073053662575.883401962
#Sta/Elev= 30
       0 2819.09     5.9 2818.37    17.6 2818.15      26 2819.77    30.1 2820.33
    34.1 2820.42    38.1 2818.66    46.2 2813.14    50.2 2811.25    54.2 2810.51
    62.3 2810.14    66.3 2809.63    70.3 2807.23    74.3 2803.73    77.5 2802.24
    78.4 2801.83    82.4 2801.37    94.5 2801.61    97.2 2802.21    98.5 2802.46
   102.5 2804.61   106.5 2807.81   110.6 2808.54   114.2 2808.68   129.9 2808.33
   143.3 2809.27   148.2 2810.32   151.9 2811.77   154.7 2813.35     164 2819.48
#Mann= 3 ,-1,0
       0      .1       0    77.5    .045       0    97.2      .1       0
Bank Sta=77.5,97.2
XS Rating Curve= 0 ,0
Exp/Cntr(USF)=0,0
Exp/Cntr=0.3,0.1

Type RM Length L Ch R = 1 ,6007    ,308.6,309,311.4
XS GIS Cut Line= 3
2322587.78413793662846.7312384172322641.95370522662776.272920122
 2322628.9900481662635.169217774
#Sta/Elev= 30
       0 2822.75       2 2821.69     7.1 2819.82      12 2816.43    15.6  2813.3
    22.1 2808.13    32.2 2800.48    38.5 2793.81    41.3 2791.71    42.3 2791.32
    44.2 2791.03    52.4 2790.73    57.5 2790.96    59.52791.309    64.1 2792.34
    69.8 2794.82    72.7 2795.75    88.9 2796.01   108.1 2796.75   132.2 2798.14
   144.2 2799.12   152.3 2799.31   160.3 2798.96   168.3 2799.96   180.4 2802.03
   196.5    2802   216.5 2802.53   220.5 2803.45   224.5 2805.34   230.6 2809.51
#Mann= 3 ,-1,0
       0      .1       0    42.3    .045       0    59.5      .1       0
Bank Sta=42.3,59.5
XS Rating Curve= 0 ,0
Exp/Cntr(USF)=0,0
Exp/Cntr=0.3,0.1

Type RM Length L Ch R = 1 ,5698    ,498.5,494,489.3
XS GIS Cut Line= 4
2322765.30593783 662878.165612672322829.74120633662856.346262488
2322936.94212981662733.6411075092322953.09129954662707.517306866
#Sta/Elev= 30
       0 2792.83    15.8 2791.36    31.4  2789.1    47.2 2788.55    57.9 2786.65
    80.5 2786.41    98.8  2785.3   104.1 2785.55   109.4 2784.93   114.7 2782.56
     120 2781.18   130.7 2780.99   137.2    2782   141.3 2782.22   151.4  2780.4
   157.2 2780.89   159.9 2780.56   162.5 2779.74   168.4 2775.74   176.9  2775.1
   181.2    2775   194.4 2775.17     205 2777.41   208.1  2779.1   211.6 2781.65
   219.4 2788.99   230.8 2797.37   240.9 2806.36     255 2816.73   261.7 2820.16
#Mann= 3 ,-1,0
       0      .1       0   176.9    .045       0   194.4      .1       0
Bank Sta=176.9,194.4
XS Rating Curve= 0 ,0
Exp/Cntr(USF)=0,0
Exp/Cntr=0.3,0.1

Type RM Length L Ch R = 1 ,5204    ,194,194,192.3
XS GIS Cut Line= 6
2323147.64710034662948.0864910042323234.48129552662902.674968439
2323327.62664774662835.775711321 2323336.9640559662766.440400743
2323297.76127187662760.6731114162323263.93741826662724.404058909
#Sta/Elev= 30
       0 2780.62    11.3 2778.39    36.9 2776.43    57.9  2772.6    78.4  2772.2
    95.7 2773.84     109 2772.43   119.1 2772.55   125.3 2770.52   131.9 2770.23
   137.7 2768.75   150.1  2769.3   162.9 2766.89   174.9 2767.54   191.9 2766.02
     204 2762.02   210.5 2761.17   216.3  2759.6   228.4 2749.14   238.22745.887
   241.3 2745.19   254.52745.914   264.7 2747.47   272.8 2751.46   276.8 2752.19
   288.4 2752.18   326.8 2754.01   333.5 2755.42   349.5 2762.91   372.8 2779.39
#Mann= 3 ,-1,0
       0      .1       0   238.2    .045       0   254.5      .1       0
Bank Sta=238.2,254.5
XS Rating Curve= 0 ,0
Exp/Cntr(USF)=0,0
Exp/Cntr=0.3,0.1

Type RM Length L Ch R = 1 ,5010    ,301.4,294.7,287.1
XS GIS Cut Line= 3
2323519.84229536662955.4317043032323518.90696657662791.281500391
2323467.46388272662694.942634278
#Sta/Elev= 30
       0  2766.8    13.8 2756.81    18.3  2754.1    22.3 2752.66    30.3 2747.22
    34.3 2745.51    42.8 2740.72    46.3 2739.98    82.3 2739.18    94.3 2737.62
   102.3 2735.44   109.3 2735.02   117.3 2734.61   125.2 2735.14   126.3  2735.2
   130.3 2737.12   138.3 2742.84   158.3 2746.95   166.5 2749.69   171.1 2749.65
   175.6 2747.89   180.1 2745.22   184.7 2744.55   197.3 2745.94   206.2 2747.75
     230 2748.26   235.7 2749.16   253.5 2753.35   259.4 2755.66   273.4 2762.73
#Mann= 3 ,-1,0
       0      .1       0   109.3    .045       0   125.2      .1       0
#XS Ineff= 2 , 0
           95.09 2743.14
Permanent Ineff=
       F       F
Bank Sta=109.3,125.2
XS Rating Curve= 0 ,0
Exp/Cntr(USF)=0,0
Exp/Cntr=0.3,0.1

Type RM Length L Ch R = 1 ,4716    ,180.8,183.4,183.1
XS GIS Cut Line= 2
2323817.77951815662750.7500718882323666.50551644 662640.42870047
#Sta/Elev= 30
       0 2760.52       2 2758.93    10.9 2750.63    16.2 2745.33    25.2 2738.12
    26.7 2736.69    31.7 2733.71    36.6  2731.3    50.9 2725.57    56.4 2725.58
    61.4  2726.8    62.4  2726.8    70.6 2725.15    79.6 2721.72    86.1 2721.09
    92.62721.277     101 2720.81     106 2721.01     1082721.357   119.7  2723.3
   130.7 2728.35     134 2729.12   142.6 2729.64   148.3 2730.52   156.9 2730.21
   170.3 2731.84   175.3 2733.99   182.6 2737.77   185.2 2738.85   187.2 2739.29
#Mann= 3 ,-1,0
       0      .1       0    92.6    .045       0     108      .1       0
Bank Sta=92.6,108
XS Rating Curve= 0 ,0
Exp/Cntr(USF)=0,0
Exp/Cntr=0.3,0.1

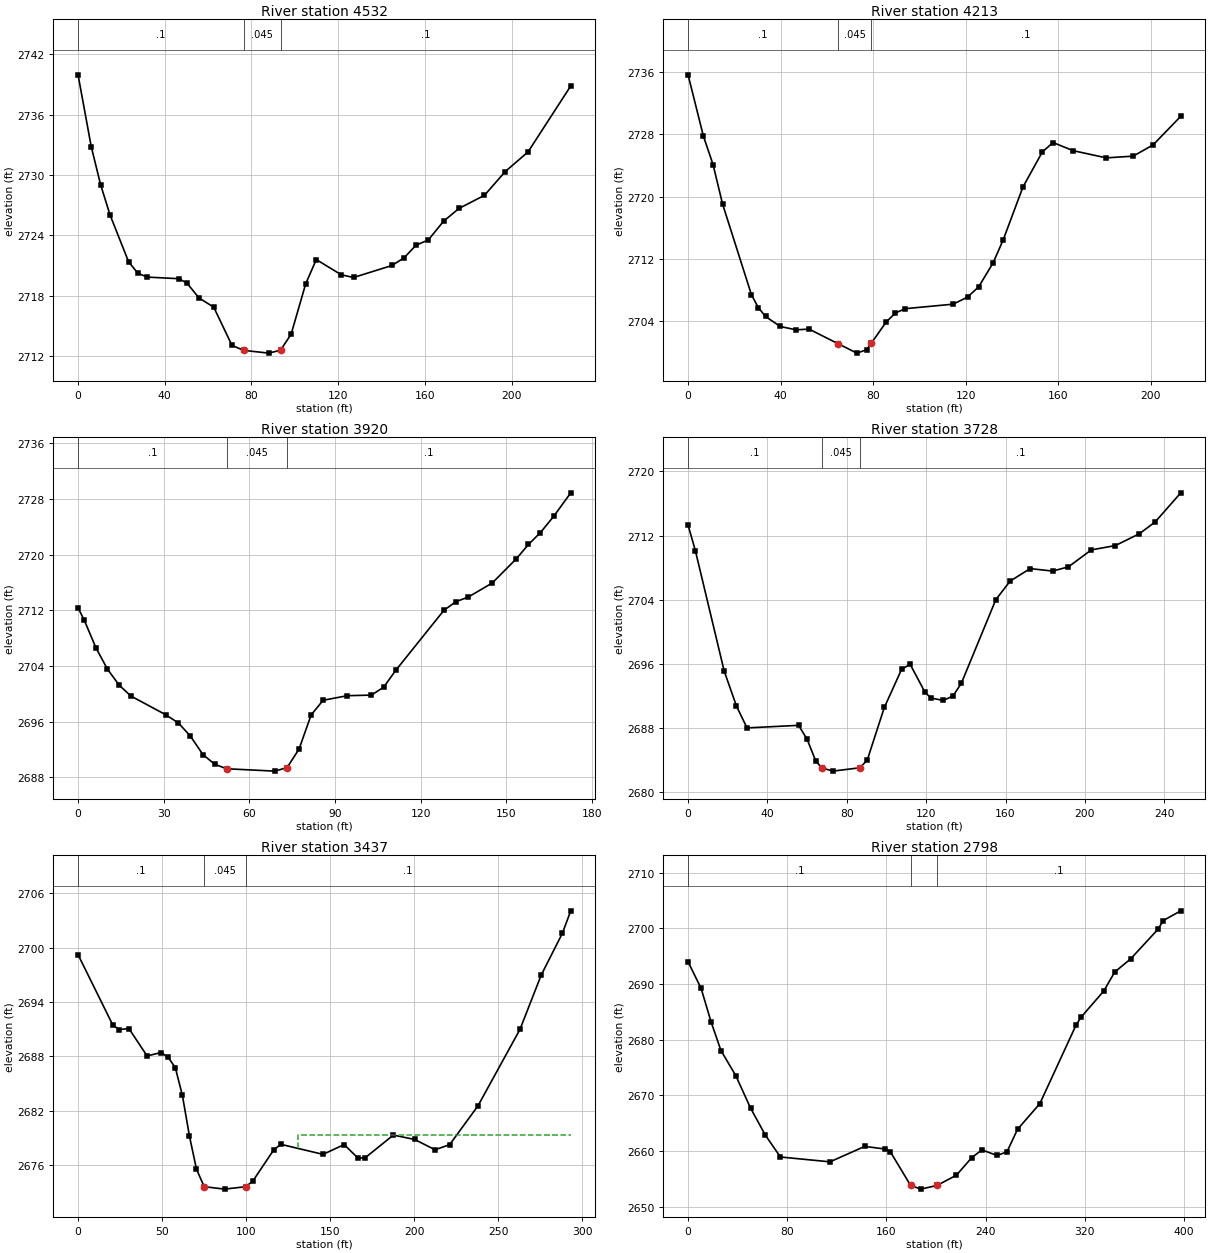
Type RM Length L Ch R = 1 ,4532    ,312.3,319.8,328.7
XS GIS Cut Line= 5
2323885.55585508662630.872611668 2323877.6055603662610.295378129
2323885.55585508662589.2504801922323804.18224972662505.070888442
2323749.93317948662468.125400952
#Sta/Elev= 30
       0 2739.95     6.1  2732.8    10.4 2729.05    14.7 2726.07    23.3  2721.4
    27.5 2720.27    31.8 2719.87    46.5 2719.71    50.2 2719.28    55.8  2717.8
    62.6 2716.88      71 2713.09    76.42712.595      88 2712.32    93.42712.611
    98.3  2714.2     105 2719.19   109.9 2721.61   121.4  2720.1   127.1 2719.83
   144.8 2721.02   150.4 2721.78   155.9 2723.03   161.6 2723.56   168.6 2725.41
   175.7 2726.68   187.5 2727.99     197 2730.33   207.6  2732.3   227.3 2738.85
#Mann= 3 ,-1,0
       0      .1       0    76.4    .045       0    93.4      .1       0
Bank Sta=76.4,93.4
XS Rating Curve= 0 ,0
Exp/Cntr(USF)=0,0
Exp/Cntr=0.3,0.1

Type RM Length L Ch R = 1 ,4213    ,297.1,292.4,288.5
XS GIS Cut Line= 3
2324129.20900675662591.5888021852324159.13952826662482.622997309
2324121.25871197662390.025446384
#Sta/Elev= 30
       0 2735.65     6.6  2727.8    10.8 2724.12    14.9 2719.06    27.4 2707.39
    30.4 2705.72    33.5  2704.6    39.8 2703.32    46.7 2702.88    52.3 2702.98
    64.7 2701.12      73 2699.89    77.2 2700.33    79.2 2701.16    85.7 2703.91
    89.6 2705.04    93.8  2705.6   114.6 2706.18   120.8 2707.09   125.6  2708.4
   131.8 2711.45   136.2 2714.42   144.8 2721.26   153.2 2725.76   157.8 2726.95
   166.4 2725.91   180.8 2724.98   192.4  2725.2     201 2726.64     213 2730.32
#Mann= 3 ,-1,0
       0      .1       0    64.7    .045       0    79.2      .1       0
Bank Sta=64.7,79.2
XS Rating Curve= 0 ,0
Exp/Cntr(USF)=0,0
Exp/Cntr=0.3,0.1

Type RM Length L Ch R = 1 ,3920    ,193,192.3,191.7
XS GIS Cut Line= 3
 2324416.8226119662523.3097999882324421.96692028662497.588258064
2324374.73281602662359.159596075
#Sta/Elev= 30
       0 2712.36     2.2 2710.56     6.3 2706.58    10.3 2703.54    14.4 2701.24
    18.5 2699.68    30.9 2696.94    35.1 2695.81    39.3 2693.94    43.7 2691.27
    47.8 2689.88      52 2689.22    68.9 2688.88    73.2 2689.39    77.4 2692.08
    81.6 2696.96    85.8 2699.07    94.3 2699.73   102.7 2699.81     107 2700.95
   111.2 2703.36   128.1 2712.01   132.3 2713.25   136.6 2713.91     145 2715.93
   153.5 2719.44   157.7 2721.48   161.9 2723.19   166.6 2725.56   172.5  2728.9
#Mann= 3 ,-1,0
       0      .1       0      52    .045       0    73.2      .1       0
Bank Sta=52,73.2
XS Rating Curve= 0 ,0
Exp/Cntr(USF)=0,0
Exp/Cntr=0.3,0.1

Type RM Length L Ch R = 1 ,3728    ,290.1,291.2,291.9
XS GIS Cut Line= 3
 2324616.5153101662460.6427705742324543.55966392  662283.3979635
2324487.43993609662275.915333123
#Sta/Elev= 30
       0  2713.3     3.7  2710.1    18.2  2695.1    24.4 2690.73    29.7 2688.01
    55.7 2688.33      60 2686.59    64.3 2683.91    67.3 2683.04      73 2682.62
    86.6 2683.04    90.3    2684    98.9 2690.56   107.6 2695.31   111.9 2695.95
   119.4 2692.46   122.4 2691.74   128.6 2691.43   133.5 2691.99   137.7 2693.57
   155.1 2704.01   162.3 2706.32   172.4 2707.88   183.7 2707.57   191.7  2708.1
   203.2 2710.21   215.3 2710.75   227.4 2712.22   235.4  2713.7   248.3 2717.33
#Mann= 3 ,-1,0
       0      .1       0    67.3    .045       0    86.6      .1       0
Bank Sta=67.3,86.6
XS Rating Curve= 0 ,0
Exp/Cntr(USF)=0,0
Exp/Cntr=0.3,0.1

Type RM Length L Ch R = 1 ,3437    ,626.2,638.6,639.7
XS GIS Cut Line= 2
 2324886.8253325662376.4631788242324799.83975436662096.332204056
#Sta/Elev= 30
       0 2699.24    20.7 2691.46    24.4 2690.97    30.3 2691.07    41.1 2688.05
    49.5 2688.43    53.7 2687.88    57.9 2686.76    62.1  2683.7    66.3 2679.21
    70.5 2675.54    75.1 2673.61    87.2 2673.34    99.8 2673.61     104 2674.22
   116.5 2677.68   120.7 2678.29   145.8 2677.18   158.4 2678.26   166.8 2676.74
   171.1 2676.83   187.7 2679.31   200.3 2678.83   212.5 2677.69   221.2 2678.25
     238 2682.52   263.1    2691   275.7 2696.98   288.3  2701.6   293.3 2704.08
#Mann= 3 ,-1,0
       0      .1       0    75.1    .045       0    99.8      .1       0
#XS Ineff= 2 , 0
                          131.05         2679.32
Permanent Ineff=
       F       F
Bank Sta=75.1,99.8
XS Rating Curve= 0 ,0
Exp/Cntr(USF)=0,0
Exp/Cntr=0.3,0.1

Type RM Length L Ch R = 1 ,2798    ,329.2,317.5,313.4
XS GIS Cut Line= 4
2325357.84484617662379.6345705952325353.93376585662237.857908864
2325386.20017852662100.9700975372325338.28944455661996.348698879
#Sta/Elev= 30
       0    2694    10.5 2689.24    18.5 2683.25    26.5 2678.07    38.5 2673.56
    50.5 2667.69    62.4 2662.86    74.5 2658.95   114.5 2658.08   142.5 2660.85
     159 2660.38   163.1 2659.92   179.5 2653.86   187.7 2653.18   200.8 2653.84
   216.5 2655.68   228.8 2658.82     237 2660.22   249.4 2659.22   257.3 2659.89
   265.8 2663.92   283.8 2668.53     313 2682.63     317 2684.04   335.4 2688.76
   344.2 2692.16     357 2694.51     379 2699.81   383.4 2701.41   397.5 2703.15
#Mann= 3 ,-1,0
       0      .1       0   179.5    .045       0   200.8      .1       0
Bank Sta=179.5,200.8
XS Rating Curve= 0 ,0
Exp/Cntr(USF)=0,0
Exp/Cntr=0.3,0.1