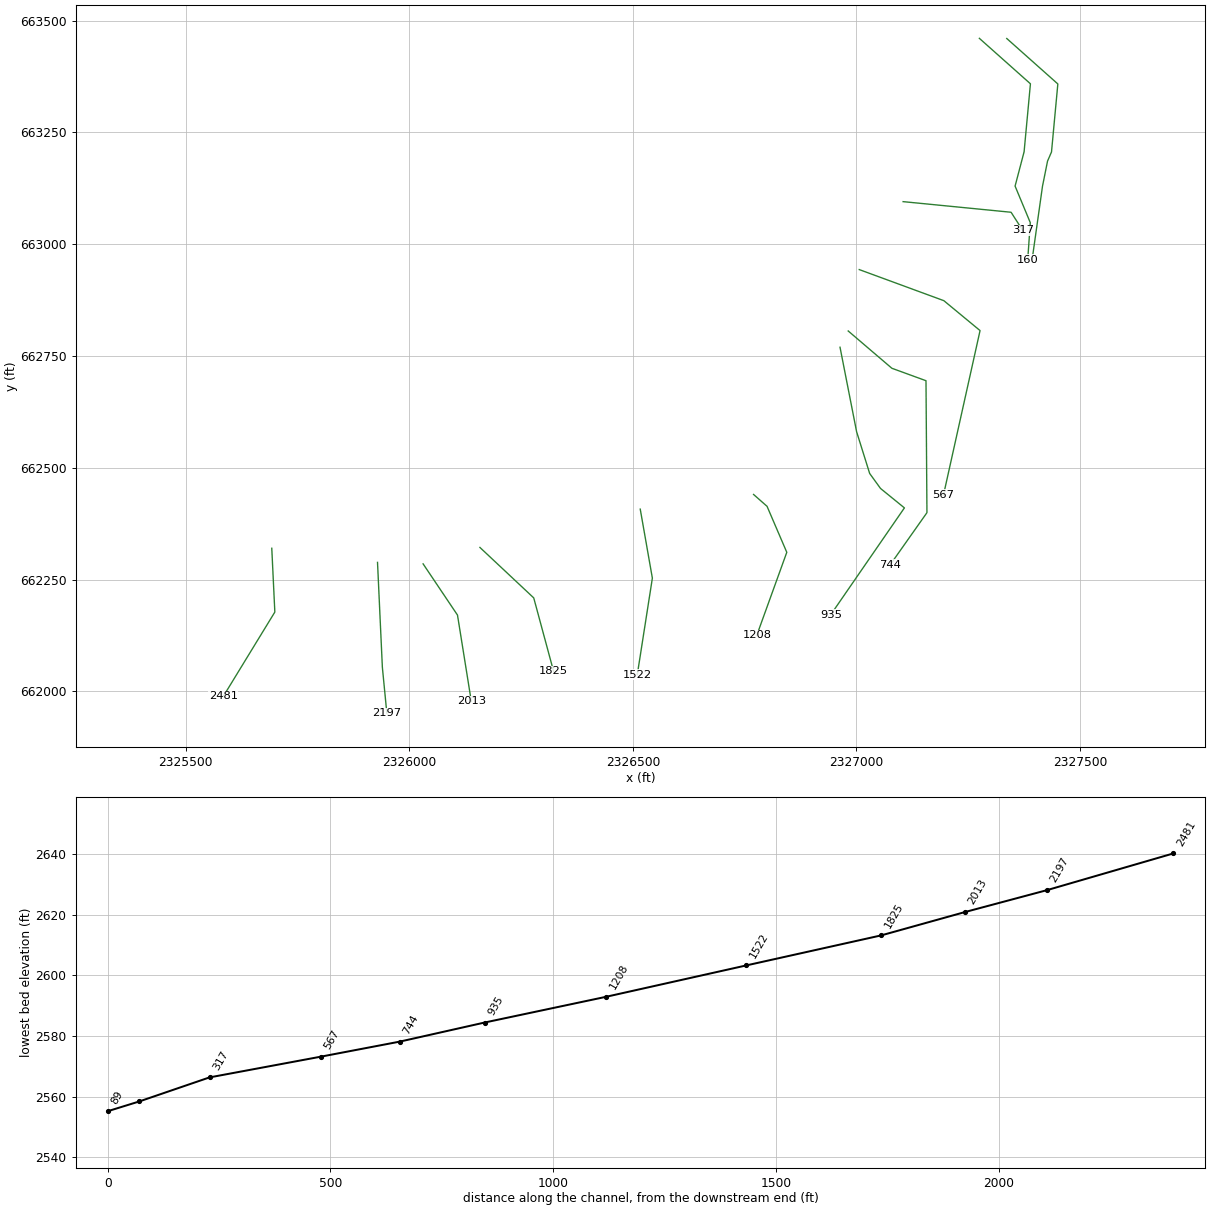
HEC-RAS study FISHHAWKCK.prj: FISHHAWKCK

--- FISHHAWKCK.g01 (geometry) --- (continued)

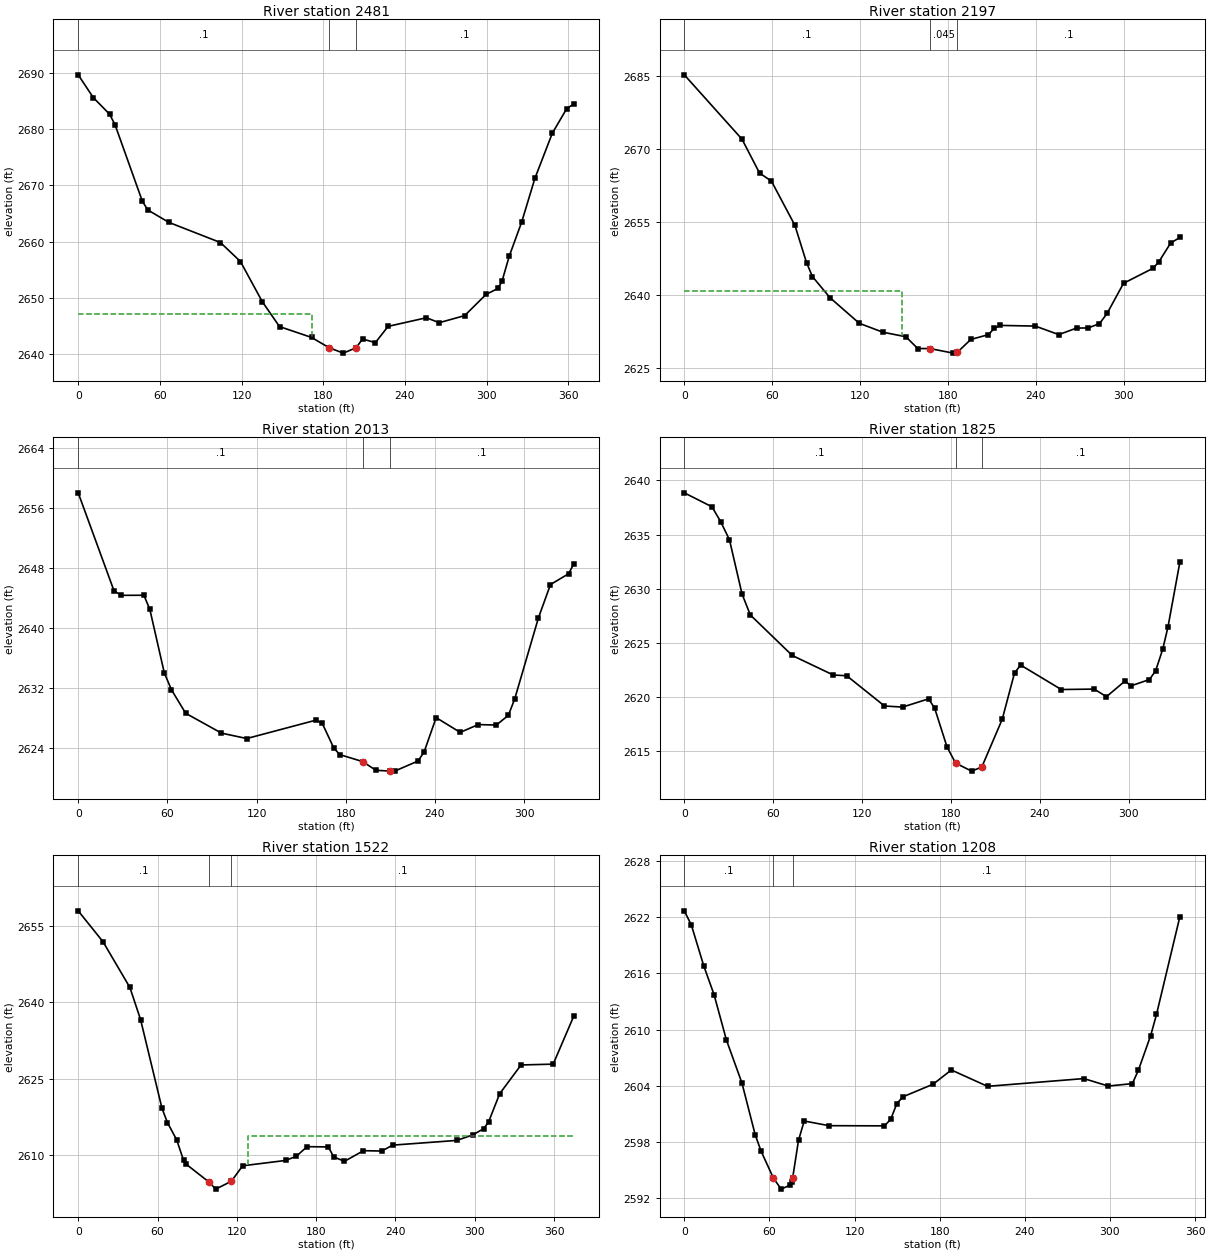
Type RM Length L Ch R = 1 ,2481    ,274.6,283.6,286.7
XS GIS Cut Line= 3
2325692.46710096662320.2252604792325699.31149153662177.470828667
2325583.93462198661988.761203052
#Sta/Elev= 30
       0 2689.62    11.1 2685.58    23.1 2682.62    27.1 2680.74    47.1  2667.2
    51.1 2665.64    66.6 2663.43   104.5 2659.85   119.2 2656.48   135.2 2649.37
   147.9 2644.93   171.4 2643.01   184.4 2641.17   194.8 2640.22   204.2 2641.18
   208.9 2642.73   218.3 2642.08   227.7 2644.97   255.8  2646.5   265.2 2645.62
   283.9 2646.88   299.6 2650.63   308.3  2651.7   311.3 2652.94   316.7 2657.45
   325.8 2663.48   335.5 2671.23   348.3 2679.25   358.9 2683.62   364.1 2684.44
#Mann= 3 ,-1,0
       0      .1       0   184.4    .045       0   204.2      .1       0
#XS Ineff= 2 , 0
          171.84 2647.25
Permanent Ineff=
       F       F
Bank Sta=184.4,204.2
XS Rating Curve= 0 ,0
Exp/Cntr(USF)=0,0
Exp/Cntr=0.3,0.1

Type RM Length L Ch R = 1 ,2197    ,182.5,184.1,184.7
XS GIS Cut Line= 3
2325928.92939848662288.5703870832325939.79438203662053.719588836
2325949.82359761661950.920129106
#Sta/Elev= 30
       0 2685.23    39.4 2672.02    51.4 2665.06    59.5 2663.41    75.5 2654.35
    83.5 2646.65    87.5 2643.82    99.5 2639.48   119.5 2634.23   135.5 2632.41
   151.3 2631.47   159.4 2629.05   167.72629.049   183.6 2628.11   186.42628.266
   195.6 2630.91   207.6  2631.9   211.6 2633.18   215.6  2633.8   239.7 2633.66
   255.7 2631.91   267.8 2633.25   275.8 2633.28   283.5 2634.17   288.7 2636.26
   299.9 2642.44   320.2 2645.55   324.1 2646.89   332.1 2650.71   338.4 2651.85
#Mann= 3 ,-1,0
       0      .1       0   167.7    .045       0   186.4      .1       0
#XS Ineff= 2 , 0
          148.54 2640.91
Permanent Ineff=
       F       F
Bank Sta=167.7,186.4
XS Rating Curve= 0 ,0
Exp/Cntr(USF)=0,0
Exp/Cntr=0.3,0.1

Type RM Length L Ch R = 1 ,2013    ,185.7,188,188.1
XS GIS Cut Line= 3
2326030.89309024662285.2273152222326107.78374305662170.727103977
2326138.70715776661977.664703995
#Sta/Elev= 30
       0 2658.02    24.1 2644.94      29 2644.34    44.2 2644.35    48.2 2642.46
    57.9 2634.01    62.7 2631.75    72.3  2628.6    96.4 2625.95   113.4 2625.23
   159.7 2627.67   164.1 2627.29   171.9 2623.98   175.9 2623.09   191.32622.156
   200.3 2620.99   209.5 2620.89   212.9 2620.88   228.6 2622.23   232.7 2623.44
   240.8 2628.02     257 2626.05   269.1 2627.09   281.3 2627.03   289.4 2628.33
   293.7 2630.55   309.6 2641.33   317.7 2645.78   329.9 2647.22   333.4 2648.55
#Mann= 3 ,-1,0
       0      .1       0   191.3    .045       0   209.5      .1       0
Bank Sta=191.3,209.5
XS Rating Curve= 0 ,0
Exp/Cntr(USF)=0,0
Exp/Cntr=0.3,0.1

Type RM Length L Ch R = 1 ,1825    ,301.5,303.1,300.4
XS GIS Cut Line= 3
2326157.92982097662322.0011056942326278.28040797 662209.17243038
2326322.57611013662045.361909183
#Sta/Elev= 30
       0 2638.86    18.7 2637.57    24.6 2636.19    30.5 2634.53      39 2629.52
    44.6 2627.59    72.9 2623.85   100.6 2622.05   109.7 2621.98   135.2 2619.19
   147.4 2619.09     165 2619.85   169.1 2618.98   177.4 2615.42   183.22613.923
     194 2613.18   200.92613.554   214.7 2617.96     223 2622.23   227.1 2622.97
   254.6 2620.71   276.8 2620.75   285.1 2620.05   297.6 2621.49   301.7 2621.05
   314.1 2621.63   318.3 2622.43   323.1 2624.43   326.6 2626.45   334.7 2632.48
#Mann= 3 ,-1,0
       0      .1       0   183.2    .045       0   200.9      .1       0
Bank Sta=183.2,200.9
XS Rating Curve= 0 ,0
Exp/Cntr(USF)=0,0
Exp/Cntr=0.3,0.1

Type RM Length L Ch R = 1 ,1522    ,311.7,314.3,315.4
XS GIS Cut Line= 3
2326516.44754771662407.6686722262326543.57208283662253.339420684
2326509.90024613662037.746132925
#Sta/Elev= 30
       0 2657.99    18.8  2651.9    39.1 2642.92    47.2 2636.59    63.4 2619.13
    67.5 2616.36    74.5 2612.95    79.7 2608.92    81.4 2608.22    98.6 2604.72
   104.1 2603.26   115.9 2604.82   124.4 2607.85   156.9  2608.9     165 2609.72
   173.1 2611.61   189.2 2611.56   193.3 2609.59   201.4 2608.73   215.8 2610.82
   229.7 2610.75   237.8 2611.91   286.4 2612.84   298.6 2613.94   306.7 2615.15
   310.4 2616.45   318.8 2622.01     335 2627.68   359.3 2627.84   374.9  2637.3
#Mann= 3 ,-1,0
       0      .1       0    98.6    .045       0   115.9      .1       0
#XS Ineff= 2 , 0
                          128.52         2613.67
Permanent Ineff=
       F       F
Bank Sta=98.6,115.9
XS Rating Curve= 0 ,0
Exp/Cntr(USF)=0,0
Exp/Cntr=0.3,0.1

Type RM Length L Ch R = 1 ,1208    ,276.2,272.9,271.8
XS GIS Cut Line= 4
2326769.86851469662440.4902430862326800.00688704662413.989260499
2326844.17519136662311.1030928042326777.14329422662125.596214689
#Sta/Elev= 30
       0  2622.7       5 2621.17    13.7 2616.82      21 2613.72    29.7 2608.87
    40.6 2604.29      50 2598.72    54.1 2596.99    62.8  2594.1    68.3 2592.92
    74.4 2593.34    75.8 2593.65    76.42594.156    80.5 2598.14    84.5 2600.21
     102 2599.71   141.1 2599.69   145.5  2600.4   149.8 2602.07   154.1  2602.8
   175.4 2604.15   188.2 2605.67   213.7 2603.92   281.6 2604.75   298.8 2603.95
   315.8 2604.21     320 2605.63   328.7 2609.35   332.8 2611.61   349.3 2622.09
#Mann= 3 ,-1,0
       0      .1       0    62.8    .045       0    76.4      .1       0
Bank Sta=62.8,76.4
XS Rating Curve= 0 ,0
Exp/Cntr(USF)=0,0
Exp/Cntr=0.3,0.1

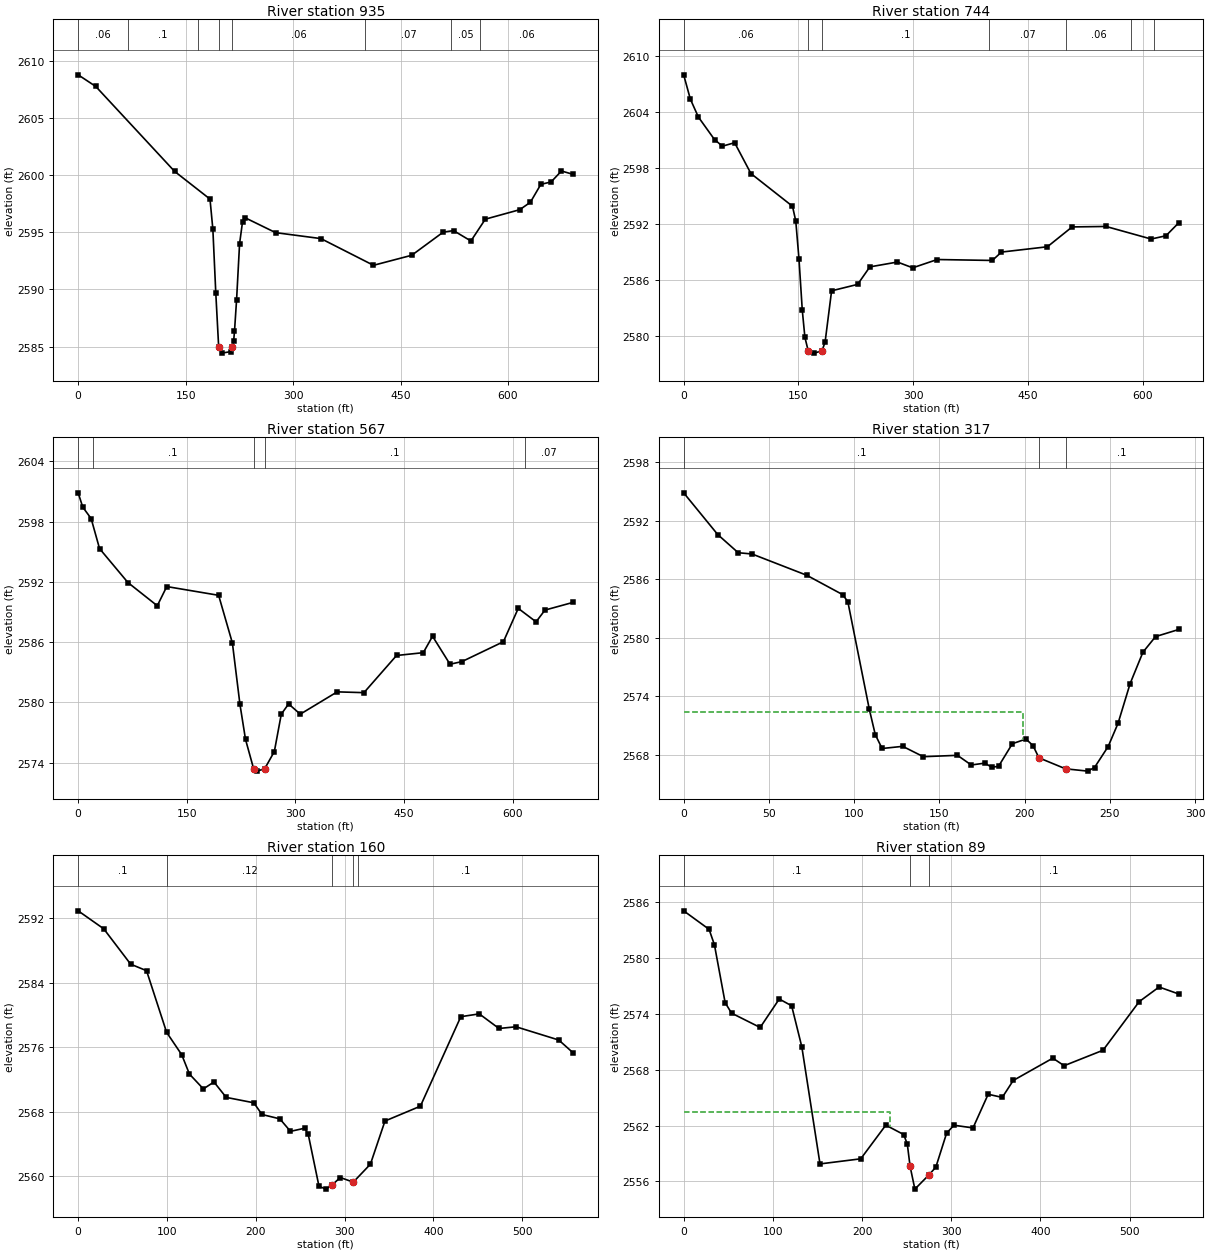
Type RM Length L Ch R = 1 ,935     ,178.6,190.2,196.2
XS GIS Cut Line= 6
2326963.21689869662769.6959287292327000.28220692662580.805415649
2327029.50677686662487.4293506922327053.74178609 662453.92801441
2327107.20136526662410.4475566822326942.54586141662171.661436374
#Sta/Elev= 30
       0 2608.79    24.6 2607.77   134.5 2600.34     184 2597.91     188 2595.27
   192.1 2589.67   196.12584.969   200.4 2584.42   212.8 2584.55   214.9    2585
     217 2585.47   218.2 2586.33   221.1 2589.08   225.3 2594.01   229.4 2595.91
   233.5 2596.26   275.6 2594.97   338.8 2594.45   412.2 2592.11   465.6 2592.99
   509.4 2595.01   523.9 2595.15   548.2 2594.24   568.3 2596.15   616.3 2596.98
   631.2 2597.63   645.8  2599.2   660.1 2599.41   674.6 2600.37     691 2600.07
#Mann= 8 ,-1,0
       0     .06       0      70      .1       0  167.36     .06       0
   196.1    .045       0   214.9     .06       0  400.93     .07       0
  520.93     .05       0  560.93     .06       0
Bank Sta=196.1,214.9
XS Rating Curve= 0 ,0
Exp/Cntr(USF)=0,0
Exp/Cntr=0.3,0.1

Type RM Length L Ch R = 1 ,744     ,180.8,177.3,174.5
XS GIS Cut Line= 5
2326981.54291739662806.0484425672327079.19574868662722.651499056
 2327155.4647483662694.8525178862327157.60313147662399.755640848
2327075.63177674662283.570155444
#Sta/Elev= 30
       0 2608.01     8.7 2605.41    19.2 2603.48    40.3 2601.06    50.6 2600.35
    66.6 2600.72    87.9 2597.41   142.2  2593.9   146.5 2592.31   150.7 2588.22
     155 2582.74   158.4 2579.84   162.72578.385   170.9 2578.13   180.8 2578.39
   184.8 2579.31   193.3 2584.82   227.3 2585.51   243.3 2587.39   279.3 2587.91
   299.3 2587.29   331.3 2588.18   403.3 2588.08   415.3 2588.98   475.3 2589.55
   507.6 2591.68   551.9 2591.73   610.9 2590.38   630.2 2590.73   646.9 2592.12
#Mann= 7 ,-1,0
       0     .06       0   162.7    .045       0   180.8      .1       0
   399.6     .07       0   499.6     .06       0   584.7     .07       0
   614.7     .05       0
Bank Sta=162.7,180.8
XS Rating Curve= 0 ,0
Exp/Cntr(USF)=0,0
Exp/Cntr=0.3,0.1

Type RM Length L Ch R = 1 ,567     ,246.5,249.8,255.5
XS GIS Cut Line= 4
2327006.21792315662943.3537617192327195.41643381662873.834308966
2327276.37579651662806.9548354322327194.53644074662439.117730995
#Sta/Elev= 30
       0 2600.86     6.3 2599.44    17.9  2598.3    29.5 2595.31    68.7 2591.93
   109.2 2589.62   122.3 2591.53   193.9 2590.66   212.9 2585.91   223.3 2579.82
     231 2576.32   242.3 2573.37   246.6 2573.16   257.42573.387   270.8 2575.11
   280.4 2578.83   290.5 2579.85   306.6 2578.83   357.6 2581.05   394.5 2580.97
   439.5 2584.67   476.4 2584.95   489.2 2586.58   513.3  2583.8   529.7 2584.06
     587 2586.04   607.5 2589.36   632.1 2588.02   644.4 2589.19   683.4 2589.96
#Mann= 5 ,-1,0
       0     .06       0      20      .1       0   242.3    .045       0
   257.4      .1       0  616.58     .07       0
Bank Sta=242.3,257.4
XS Rating Curve= 0 ,0
Exp/Cntr(USF)=0,0
Exp/Cntr=0.3,0.1

Type RM Length L Ch R = 1 ,317     ,171.3,157.4,141.5
XS GIS Cut Line= 3
  2327104.297747663095.2928360482327345.74182586663071.561153083
2327371.53713343663031.320473273
#Sta/Elev= 30
       0 2594.85      20 2590.57      32 2588.71    40.1 2588.58    72.2  2586.4
    93.3 2584.41    96.3 2583.69   108.9 2572.66   112.4 2570.06   116.4 2568.64
   128.5 2568.86   140.6  2567.8   160.6 2567.94   168.7 2566.95   176.7 2567.14
   180.7 2566.72   184.7 2566.81   192.8 2569.13   200.8 2569.61   204.9 2568.94
   208.42567.684     2242566.558     237 2566.32     241 2566.69     249 2568.84
   254.8 2571.22   261.9  2575.3   269.4 2578.51   276.8 2580.11   290.4 2580.84
#Mann= 3 ,-1,0
       0      .1       0   208.4    .045       0     224      .1       0
#XS Ineff= 2 , 0
          198.91 2572.36
Permanent Ineff=
       F       F
Bank Sta=208.4,224
XS Rating Curve= 0 ,0
Exp/Cntr(USF)=0,0
Exp/Cntr=0.3,0.1

Type RM Length L Ch R = 1 ,160     ,71.5,71.2,74.4
XS GIS Cut Line= 6
2327274.80447783663460.4860500752327389.02757868663358.846850164
2327374.85668879663206.7875160042327354.70784884663130.048651232
2327388.70803328663048.2995088532327382.93835995662964.942439024
#Sta/Elev= 30
       0 2592.89    28.8 2590.66    59.1 2586.28      77 2585.47    99.6 2577.83
   116.6 2575.06   125.3 2572.66     141 2570.82   152.9 2571.68   166.7 2569.77
   197.8  2569.1     207 2567.65   227.1 2567.11   239.1 2565.56   255.1 2565.95
   259.1 2565.18   271.2 2558.75   279.2  2558.4   286.22558.947   295.2 2559.84
   309.82559.265   329.1 2561.49   345.5 2566.84   385.4 2568.68   430.9 2579.77
   451.7 2580.12   473.9 2578.31   493.1 2578.52   541.2 2576.88   557.5 2575.28
#Mann= 5 ,-1,0
       0      .1       0     100     .12       0   286.2    .045       0
   309.8     .12       0  315.67      .1       0
Bank Sta=286.2,309.8
XS Rating Curve= 0 ,0
Exp/Cntr(USF)=0,0
Exp/Cntr=0.3,0.1

Type RM Length L Ch R = 1 ,89      ,,,
XS GIS Cut Line= 6
2327336.09364136 663460.113851842327450.31674221663358.474651929
2327436.14585232663206.4153177692327427.25710617663185.867305587
2327415.99701237663129.676452997 2327392.2371994662961.597776089
#Sta/Elev= 30
       0 2585.08    28.5 2583.09    34.5 2581.43    46.5 2575.21    53.7 2574.08
    85.8 2572.54   107.2  2575.6   121.1 2574.87   132.5 2570.46   152.9 2557.87
   198.6 2558.42   226.7 2562.04   246.7 2561.03   250.8 2560.01   253.92557.623
   259.3 2555.16   274.92556.675   282.8 2557.52   294.9 2561.18   303.1 2562.03
   324.5 2561.74   341.5 2565.36   357.3 2565.02   369.6 2566.84     414 2569.24
   426.7 2568.43   470.3 2570.09   510.9 2575.32   533.2 2576.89   555.2 2576.14
#Mann= 3 ,-1,0
       0      .1       0   253.9    .045       0   274.9      .1       0
#XS Ineff= 2 , 0
          231.69  2563.4
Permanent Ineff=
       F       F
Bank Sta=253.9,274.9
XS Rating Curve= 0 ,0
Exp/Cntr(USF)=0,0
Exp/Cntr=0.3,0.1
LCMann Table=0

Chan Stop Cuts=-1
Use User Specified Reach Order=0
Composite Channel Slope=5